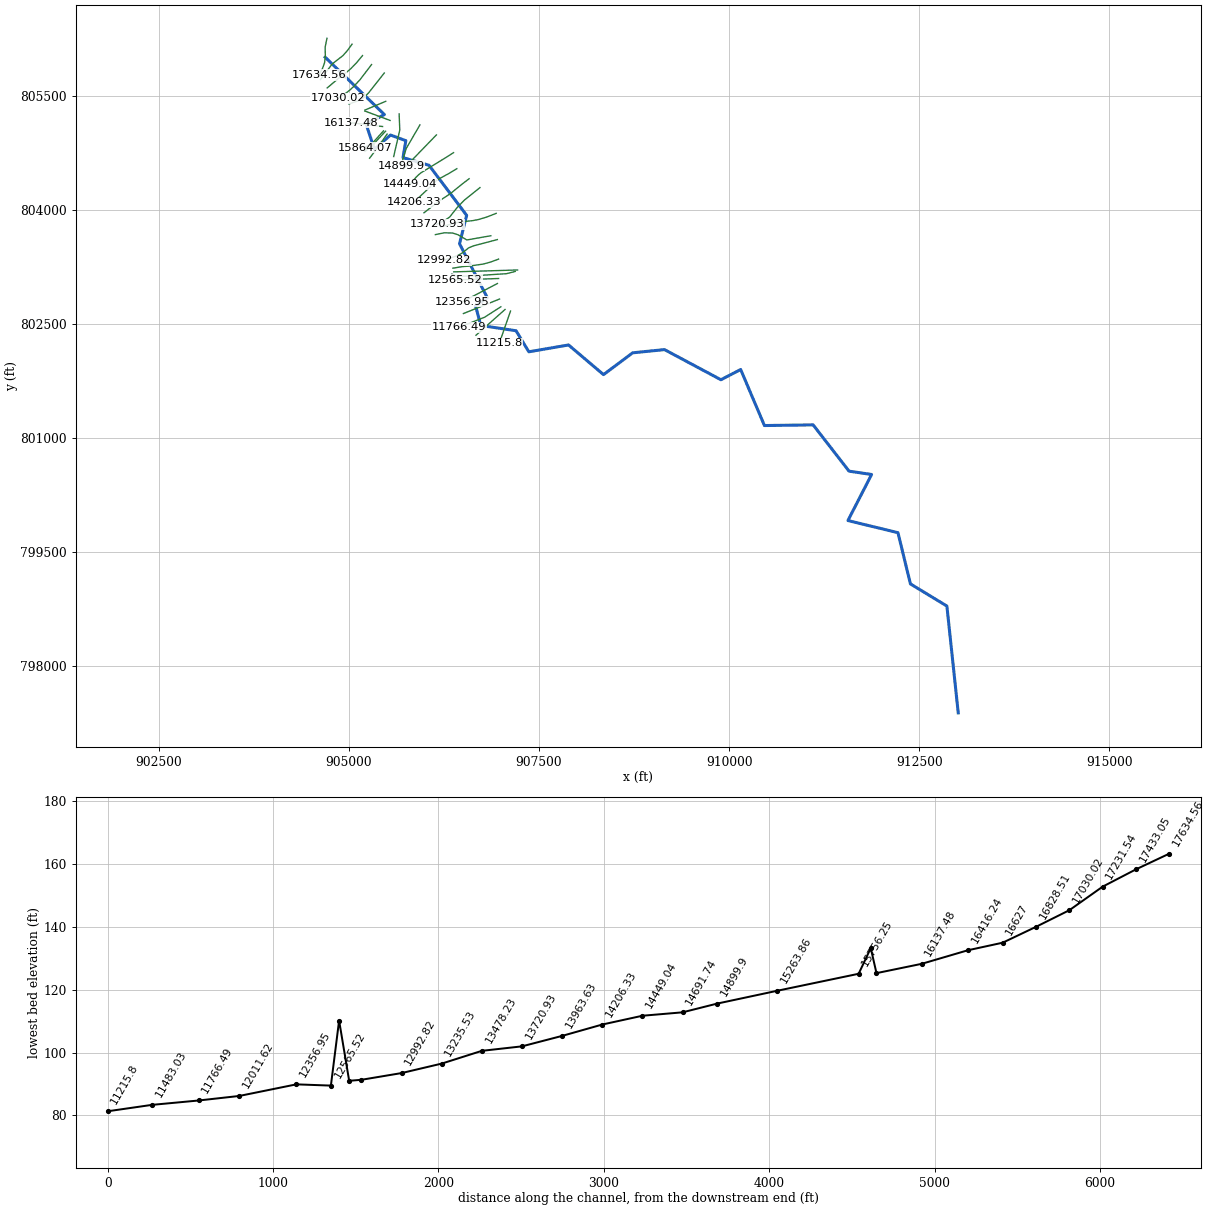
--- 13108_ras.prj (project) ---

Proj Title=13108
Current Plan=p01
Default Exp/Contr=0.3,0.1
English Units
Geom File=g01
Flow File=f01
Plan File=p01
Y Axis Title=Elevation
X Axis Title(PF)=Main Channel Distance
X Axis Title(XS)=Station
BEGIN DESCRIPTION:
RFD model 13108 exported to HEC-RAS
END DESCRIPTION:

--- 13108_ras.p01 (plan) ---

Plan Title=Plan 01
Program Version=4.10
Short Identifier=Plan 01
Geom File=g01
Flow File=f01
Subcritical Flow
Calc Critical at every XS
Secant Critical Depth

--- 13108_ras.f01 (steady flow) ---

Flow Title=Flow 01
Program Version=5.01
Number of Profiles= 6
Profile Names=10yr,25yr,50yr,100yr,100plus,500yr
River Rch & RM=13108,49,17634.56
  731.77 1083.39    1392 1641.52 2396.61 3115.18
River Rch & RM=13108,49,17433.05
  943.78 1403.76 1809.49 2139.34 3123.44 3932.27
River Rch & RM=13108,49,17231.54
  948.41 1410.93 1818.98 2150.83 3140.21 3951.44
River Rch & RM=13108,49,17030.02
   951.6 1415.89 1825.55 2158.77 3151.81 3964.69
River Rch & RM=13108,49,16828.51
  955.16 1421.39 1832.84 2167.59 3164.69 3979.39
River Rch & RM=13108,49,   16627
  956.93 1424.14 1836.49    2172 3171.12 3986.73
River Rch & RM=13108,49,16416.24
  967.56 1440.62 1858.32 2198.41 3209.68 4030.68
River Rch & RM=13108,49,16137.48
   968.6 1442.24 1860.47 2201.02 3213.49 4035.06
River Rch & RM=13108,49,15864.07
 1016.67 1517.15 1959.99 2321.72  3389.7 4236.19
River Rch & RM=13108,49,15756.25
 1018.63 1520.25 1964.14 2326.79 3397.12 4244.79
River Rch & RM=13108,49,15263.86
  1057.6 1581.28  2045.5 2425.76 3541.61 4409.68
River Rch & RM=13108,49, 14899.9
  1071.5 1603.28 2074.99  2461.8 3594.23 4470.19
River Rch & RM=13108,49,14691.74
 1073.73 1606.81 2079.74 2467.62 3602.73 4480.01
River Rch & RM=13108,49,14449.04
 1082.48 1620.78 2098.57 2490.75  3636.5  4519.2
River Rch & RM=13108,49,14206.33
 1095.59 1641.54 2126.44 2524.85 3686.28 4576.35
River Rch & RM=13108,49,13963.63
 1129.95 1696.25  2200.1 2615.23 3818.24 4728.33
River Rch & RM=13108,49,13720.93
 1146.04 1721.89 2234.65 2657.65 3880.17  4799.5
River Rch & RM=13108,49,13478.23
 1149.98 1728.21 2243.19 2668.17 3895.53 4817.23
River Rch & RM=13108,49,13235.53
 1156.93 1739.35 2258.26 2686.73 3922.63 4848.54
River Rch & RM=13108,49,12992.82
 1161.05 1746.02 2267.31 2697.92 3938.97 4867.55
River Rch & RM=13108,49,12750.12
 1169.02 1758.88 2284.77 2719.49 3970.46 4904.14
River Rch & RM=13108,49,12676.01
 1169.31 1759.35 2285.41 2720.29 3971.62  4905.5
River Rch & RM=13108,49,12615.13
 1171.65 1763.14 2290.56 2726.66 3980.92 4916.32
River Rch & RM=13108,49,12356.95
 1194.88 1800.46 2341.12 2789.01 4071.95 5021.33
River Rch & RM=13108,49,12011.62
 1199.56 1808.02 2351.38 2801.69 4090.47 5042.76
River Rch & RM=13108,49,11766.49
 1204.51 1816.02 2362.25 2815.14 4110.11  5065.5
River Rch & RM=13108,49,11483.03
 1212.07 1828.25 2378.86 2835.68  4140.1 5100.19
River Rch & RM=13108,49, 11215.8
 1220.51 1841.87 2397.37 2858.56  4173.5 5138.78
River Rch & RM=13108,49,11034.79
 1225.16 1849.37 2407.56 2871.17 4191.91 5160.02
River Rch & RM=13108,49,10758.95
 1226.32 1851.25 2410.11 2874.32  4196.5 5165.33
River Rch & RM=13108,49,10390.74
 1226.61 1851.72 2410.74  2875.1 4197.65 5166.65
River Rch & RM=13108,49,10157.85
 2023.72 3113.08 4104.85 4949.12 7225.72 8435.29
River Rch & RM=13108,49,9761.852
 2044.05 3145.78 4149.22 5003.95 7305.76 8520.42
River Rch & RM=13108,49,9495.639
 2050.82 3156.67    4164 5022.21 7332.42 8548.73
River Rch & RM=13108,49,9043.161
  2076.6  3198.1 4220.21 5091.63 7433.78 8656.17
River Rch & RM=13108,49,8630.897
 2203.43 3400.84 4494.37 5429.23 7926.68 9172.01
River Rch & RM=13108,49,8108.074
 2216.46  3421.8 4522.83  5464.4 7978.02 9225.91
River Rch & RM=13108,49,7760.243
 2220.57 3428.39 4531.77 5475.44 7994.14  9242.8
River Rch & RM=13108,49,7412.412
 2259.51 3490.92 4616.59 5580.15 8147.02 9402.63
River Rch & RM=13108,49,7064.581
  2290.7 3541.11 4684.74 5664.37 8269.99 9531.19
River Rch & RM=13108,49,6645.765
  2303.2 3561.17 4711.93 5697.95    8319 9582.21
River Rch & RM=13108,49,6526.899
  2310.3 3572.58 4727.42 5717.08 8346.94 9611.32
River Rch & RM=13108,49,6201.028
 2317.17 3583.61 4742.39 5735.55 8373.91 9639.36
Boundary for River Rch & Prof#=13108,49,1
Up Type= 0
Dn Type= 2
Boundary for River Rch & Prof#=13108,49,2
Up Type= 0
Dn Type= 2
Boundary for River Rch & Prof#=13108,49,2
Up Type= 0
Dn Type= 2
Boundary for River Rch & Prof#=13108,49,2
Up Type= 0
Dn Type= 2
Boundary for River Rch & Prof#=13108,49,2
Up Type= 0
Dn Type= 2
Boundary for River Rch & Prof#=13108,49,2
Up Type= 0
Dn Type= 2

--- 13108_ras.g01 (geometry) ---

Geom Title=13108
Program Version=4.10

River Reach=13108,49
Reach XY= 30
904688.664518953806005.018517979 905467.11676231805251.298623616
905227.329727443805125.302233229905335.531773896804795.473383445
905547.863166365804981.877712656 905749.16228202804907.987968185
905712.069585773 804685.08462606906053.653010907804584.625256246
906548.641448707803926.217134866 906454.89144871803552.519218184
906820.656041088  802842.8076359906666.026173236 802735.48590171
906734.839365366802478.300468203907198.428386602802408.731427642
907366.349782019802131.946301554907888.485198707802221.790051549
908348.427772882801831.801859999908731.333815875802118.530043383
909150.370552867802160.722391898909892.012916986801764.683864445
910151.728877071801898.914829411910464.272906395801162.317077478
911104.647322448801171.008801531911576.751451197800562.481959384
911873.115754905800518.869856299911562.343593779799913.010176047
912219.709261477799753.615997589912384.074564933799079.786239071
 912863.27155313798788.858516929913012.332155913797384.115756622

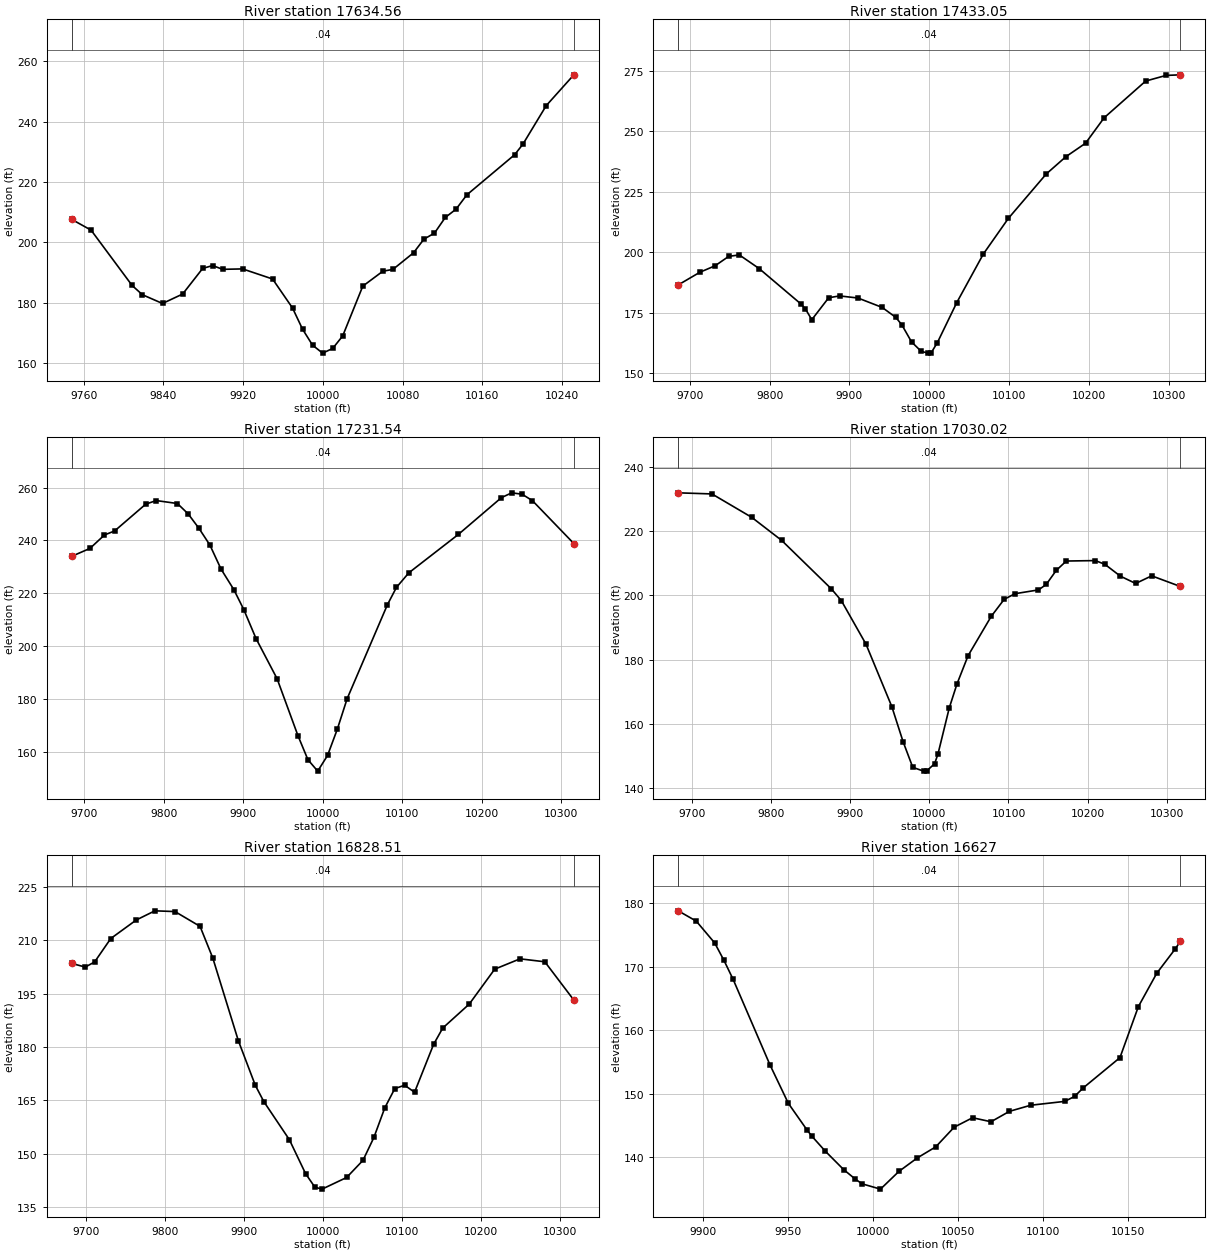
Type RM Length L Ch R = 1 ,17634.56,201.512800,201.512800,201.512800
XS GIS Cut Line= 6
904712.008590895806253.824547832904687.968787743806136.049660502
904691.141908638806015.353250446904680.490639717805932.647966763
 904652.80606895805855.547894917904604.088333601805771.578150515
#Sta/Elev= 30
9748.066207.6344 9767.44204.08089808.606185.75119818.898182.68639839.125179.7779
9859.343182.90869879.449191.40029889.457192.34729899.465191.09429919.482191.2334
9949.562187.89399969.616178.27119979.643171.26839989.672165.97539999.774163.3251
10009.88 164.86710019.96169.031110040.11185.517710060.27190.472310070.35 191.067
10091.05196.574910101.44201.087610112.07203.099710122.89208.276310133.72211.0353
10144.54215.773510192.47229.063110200.78232.550210224.22245.346910251.92255.5483
#Mann= 3 , 0 , 0
9748.066    0.04       09748.066    0.04       010251.92    0.04       0
#XS Ineff= 2 , 0
       0                               0
Bank Sta=9748.066,10251.92
Exp/Cntr=0.3,0.1

Type RM Length L Ch R = 1 ,17433.05,201.512900,201.512900,201.512900
XS GIS Cut Line= 6
 905042.24005099806176.880199587904982.158856814806094.429462202
 904921.92042289806026.261035156904798.909868778805930.699121735
904771.461113545805904.046917239904626.073560754805710.933246603
#Sta/Elev= 30
9685.468186.51789712.541191.74669731.722194.44419748.702198.31949762.034 198.914
9786.781193.29349839.097178.66529844.759176.62579852.807172.14639873.996181.2237
9887.721181.96919910.659181.10389941.032 177.2139958.145173.07379965.559170.0472
9977.793  162.969990.026159.0206    9999158.3246 10002.2158.368710010.18162.6873
10034.47179.2335 10067.8199.324610099.12214.036210146.61232.395710171.19239.5236
10195.77245.081710219.05255.594210271.12270.784210296.61273.114710314.53273.3598
#Mann= 3 , 0 , 0
9685.468    0.04       09685.468    0.04       010314.53    0.04       0
#XS Ineff= 2 , 0
       0                               0
Bank Sta=9685.468,10314.53
Exp/Cntr=0.3,0.1

Type RM Length L Ch R = 1 ,17231.54,201.512800,201.512800,201.512800
XS GIS Cut Line= 6
905179.333221217806027.091462402905100.335533426805931.580764893
905021.767619085805851.081188838904983.013078762805818.178025422
904889.902542292805748.124605306904715.096695445 805601.49902895
#Sta/Elev= 30
9683.999234.01239706.898 236.9929725.148242.0679 9737.97243.59629777.087253.7134
9790.271255.07849816.939 253.9629830.515250.04329844.216244.53129857.855238.2787
9871.876229.18789888.052221.39979900.538213.86829915.973202.91369942.481187.7299
9968.717166.22959981.265157.13379993.588152.817810006.01158.751610018.33168.7195
10030.65180.202210081.39215.743710092.73222.268710108.29227.761810170.53242.2502
10224.79256.172310237.84257.999410250.89257.474510263.94255.024710316.02238.8282
#Mann= 3 , 0 , 0
9683.999    0.04       09683.999    0.04       010316.02    0.04       0
#XS Ineff= 2 , 0
       0                               0
Bank Sta=9683.999,10316.02
Exp/Cntr=0.3,0.1

Type RM Length L Ch R = 1 ,17030.02,201.512900,201.512900,201.512900
XS GIS Cut Line= 6
905298.501713214805908.885620733905146.679291994805709.265773171
 905064.06018344805620.756561358 905010.34883307805570.979137194
  904963.8169794805534.684994498904853.077432771805467.157461001
#Sta/Elev= 30
9683.008231.9214 9725.58231.57639775.835224.28899813.526217.13269876.344202.0357
9888.907198.38789920.058 184.8369952.678165.4049 9966.91154.4791 9979.14146.5003
9992.766145.31679996.739145.396710006.71147.610310011.01150.685710025.21164.9762
10034.88172.384910048.96181.225910078.12193.450410094.56198.7795 10108.2200.5295
10137.89201.712410147.64 203.40310160.32 207.782   10173210.696510209.71210.8367
10221.68209.6835 10241.2206.000410260.58203.712510280.83206.090710316.96202.7831
#Mann= 3 , 0 , 0
9683.008    0.04       09683.008    0.04       010316.96    0.04       0
#XS Ineff= 2 , 0
       0                               0
Bank Sta=9683.008,10316.96
Exp/Cntr=0.3,0.1

Type RM Length L Ch R = 1 ,16828.51,201.512800,201.512800,201.512800
XS GIS Cut Line= 6
905465.565130316 805797.71657305905264.081109585805541.791409882
905213.937588335805489.747424624905175.463716197805460.752986379
905123.532451899805432.805884451904999.883709726805390.208013022
#Sta/Elev= 30
9681.905203.5191 9698.98202.50079710.822203.92999731.303210.52329763.627215.7432
9787.198218.32039812.657218.11349844.435213.94959860.596205.03099892.919181.8012
9914.491169.20899925.243164.64949957.566153.94799978.138144.38699989.889140.5833
    9999140.032810030.13143.307710050.85148.127910064.67154.567410078.49162.9027
10091.15 168.30910103.67169.262310116.19167.2818 10140.3180.752310151.93185.3496
10185.51 192.09210217.73 201.90810249.82204.816610281.23203.9858   10318 193.208
#Mann= 3 , 0 , 0
9681.905    0.04       09681.905    0.04       0   10318    0.04       0
#XS Ineff= 2 , 0
       0                               0
Bank Sta=9681.905,10318
Exp/Cntr=0.3,0.1

Type RM Length L Ch R = 1 ,   16627,210.756400,210.756400,210.756400
XS GIS Cut Line= 2
905484.799902083805425.438118437905212.230457638805310.854785104
#Sta/Elev= 30
9885.134178.81389895.764177.18949906.612173.74989912.069171.0043 9917.46168.0189
9939.155154.55489950.003148.48219960.851 144.3479963.677 143.3659971.698140.9708
9982.546138.05779989.482136.54379993.394135.816810004.24134.981110015.09137.7712
10025.94139.900910036.78141.638110047.63144.736810058.48146.225910069.33145.5926
10080.17147.2318 10092.7148.193710112.72148.7989 10118.5149.573710123.57150.9106
10145.26155.690310156.11163.729310166.96168.9907 10177.8172.805910180.81174.0007
#Mann= 3 , 0 , 0
9885.134    0.04       09885.134    0.04       010180.81    0.04       0
#XS Ineff= 2 , 0
       0                               0
Bank Sta=9885.134,10180.81
Exp/Cntr=0.3,0.1

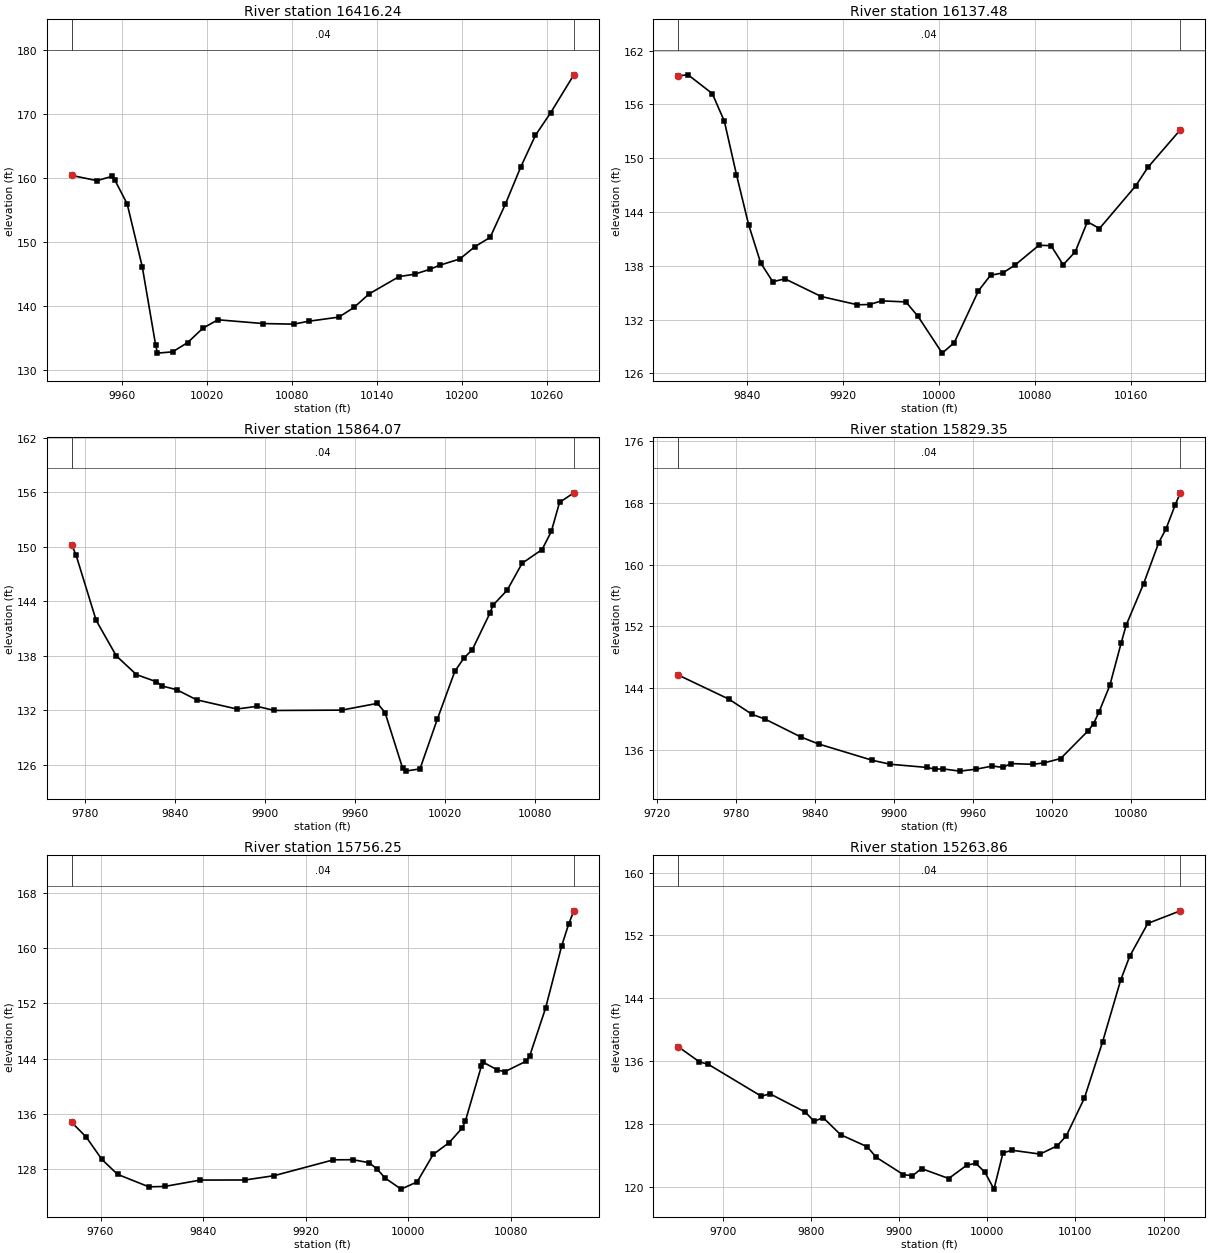
Type RM Length L Ch R = 1 ,16416.24,278.763500,278.763500,278.763500
XS GIS Cut Line= 2
905541.657540972805174.353048993905209.626290972805298.050965659
#Sta/Elev= 30
 9924.49160.36629942.266159.55259952.937160.22189954.987159.59889963.608155.9053
 9974.28 146.0319983.631133.88649984.951132.56869995.623132.766810006.29134.2224
10016.97136.462410027.64137.783110059.65137.193610080.99137.101910091.67137.5564
10113.01138.204810123.68139.718910134.35141.8387 10155.5144.543110166.37144.9121
10177.04145.666410184.14146.317410198.38 147.30410209.05149.235610219.72150.6692
10230.39155.828910241.43161.729410251.74166.656610262.41170.164710278.81176.1062
#Mann= 3 , 0 , 0
 9924.49    0.04       0 9924.49    0.04       010278.81    0.04       0
#XS Ineff= 2 , 0
       0                               0
Bank Sta=9924.49,10278.81
Exp/Cntr=0.3,0.1

Type RM Length L Ch R = 1 ,16137.48,273.410500,273.410500,273.410500
XS GIS Cut Line= 2
905443.133235416805093.840896215905028.202679861805144.188118437
#Sta/Elev= 30
9782.745159.20239790.938159.30959811.084157.22019821.158154.12349831.231148.1661
9841.304142.60899851.378138.32269861.451 136.2219871.524136.55319901.744134.5768
9931.964133.65349942.038133.68449952.111134.09089972.258133.97189982.331132.3645
10002.48128.258910012.55129.4295 10032.7135.221110042.77136.953610052.84137.2009
10062.92138.061810083.06 140.29810093.14140.242210103.21138.115510113.28139.5695
10123.36142.919210133.43142.162110163.65146.933410173.72148.984910200.72153.1726
#Mann= 3 , 0 , 0
9782.745    0.04       09782.745    0.04       010200.72    0.04       0
#XS Ineff= 2 , 0
       0                               0
Bank Sta=9782.745,10200.72
Exp/Cntr=0.3,0.1

Type RM Length L Ch R = 1 ,15864.07,34.720800,34.720800,34.720800
XS GIS Cut Line= 3
905455.337136658805037.154364431905318.010643436804883.820488563
 905206.80145874 804817.26347651
#Sta/Elev= 30
9770.837150.22239773.729 149.0819787.153141.89279800.577137.99529814.002135.9312
9827.426135.13759831.298134.6666 9840.85134.27069854.274133.15049881.123132.1367
9894.547132.43029906.244131.97659951.211132.01459975.093132.76079980.185131.7254
9991.839 125.6359993.852 125.29210003.49125.539310015.15131.0533 10026.8 136.308
 10032.8 137.74310038.46138.681310050.11142.663210052.27143.573910061.76145.2373
10071.74148.199810085.07149.710210091.22151.700310096.73154.904410106.28155.9585
#Mann= 3 , 0 , 0
9770.837    0.04       09770.837    0.04       010106.28    0.04       0
#XS Ineff= 2 , 0
       0                               0
Bank Sta=9770.837,10106.28
Exp/Cntr=0.3,0.1

Type RM Length L Ch R = 1 ,15829.35,73.098900,73.098900,73.098900
XS GIS Cut Line= 5
905483.063790972805033.294021215905350.685318749804890.064854548
905320.303374305804848.832215659905268.220040972804809.769715659
905211.796429861 804768.53707677
#Sta/Elev= 30
9736.364145.70559774.892142.57879792.444140.61499802.126140.0128 9829.36137.6943
9842.977 136.7759883.828134.66159897.445134.15179925.042133.74249931.399133.5162
 9937.69 133.5479950.112133.26239962.533133.51479974.955133.92389982.616133.7469
9989.245134.239310005.67134.144410014.25134.333710026.75134.892910047.72 138.507
10051.71139.4057 10055.8140.888310064.09144.370310072.75149.896910076.48152.1552
 10089.7157.519910101.25162.863910106.65164.592610113.64167.7013 10117.6169.2987
#Mann= 3 , 0 , 0
9736.364    0.04       09736.364    0.04       0 10117.6    0.04       0
#XS Ineff= 2 , 0
       0                               0
Bank Sta=9736.364,10117.6
Exp/Cntr=0.3,0.1

Type RM Length L Ch R = 1 ,15756.25,492.389600,492.389600,492.389600
XS GIS Cut Line= 3
905502.595040972804994.231521215905385.407540972 804827.13082677
905272.560318749804677.391243437
#Sta/Elev= 30
9737.574134.74649748.849132.63319761.063129.39349773.277127.23349797.705125.4248
9809.919125.47799837.883126.40439872.715126.41629895.417127.04219941.671129.3356
 9956.86129.35289969.382128.92419975.579 128.0299981.904126.70319994.426125.0927
10006.95126.136810019.47130.116910031.99131.837810042.04133.937810044.51134.9179
10057.03142.894710058.66143.444210069.56142.352410075.27142.092410091.89143.6106
 10094.6144.302810107.12151.301510119.64160.291210125.12163.468910129.17165.3939
#Mann= 3 , 0 , 0
9737.574    0.04       09737.574    0.04       010129.17    0.04       0
#XS Ineff= 2 , 0
       0                               0
Bank Sta=9737.574,10129.17
Exp/Cntr=0.3,0.1

Type RM Length L Ch R = 1 ,15263.86,363.959300,363.959300,363.959300
XS GIS Cut Line= 3
905661.015179861805258.988465659905669.695735416805048.484993437
905589.400596527804699.092632326
#Sta/Elev= 30
9649.725137.81689673.734135.89219683.742135.58219743.793131.52269753.802131.8162
9793.836129.48889803.844128.30799813.853128.8016 9833.87126.61219863.983 125.078
9874.244123.73439905.026121.52559915.286121.38849925.547122.30069956.329121.0346
 9976.85122.73059987.111122.97269997.372121.839410007.63119.682810017.89124.3026
10028.15124.632110059.96124.147910079.46125.207510089.72 126.48510110.24131.2957
10130.76138.426810151.28 146.29510161.54149.343810182.06153.526810218.91155.1273
#Mann= 3 , 0 , 0
9649.725    0.04       09649.725    0.04       010218.91    0.04       0
#XS Ineff= 2 , 0
       0                               0
Bank Sta=9649.725,10218.91
Exp/Cntr=0.3,0.1

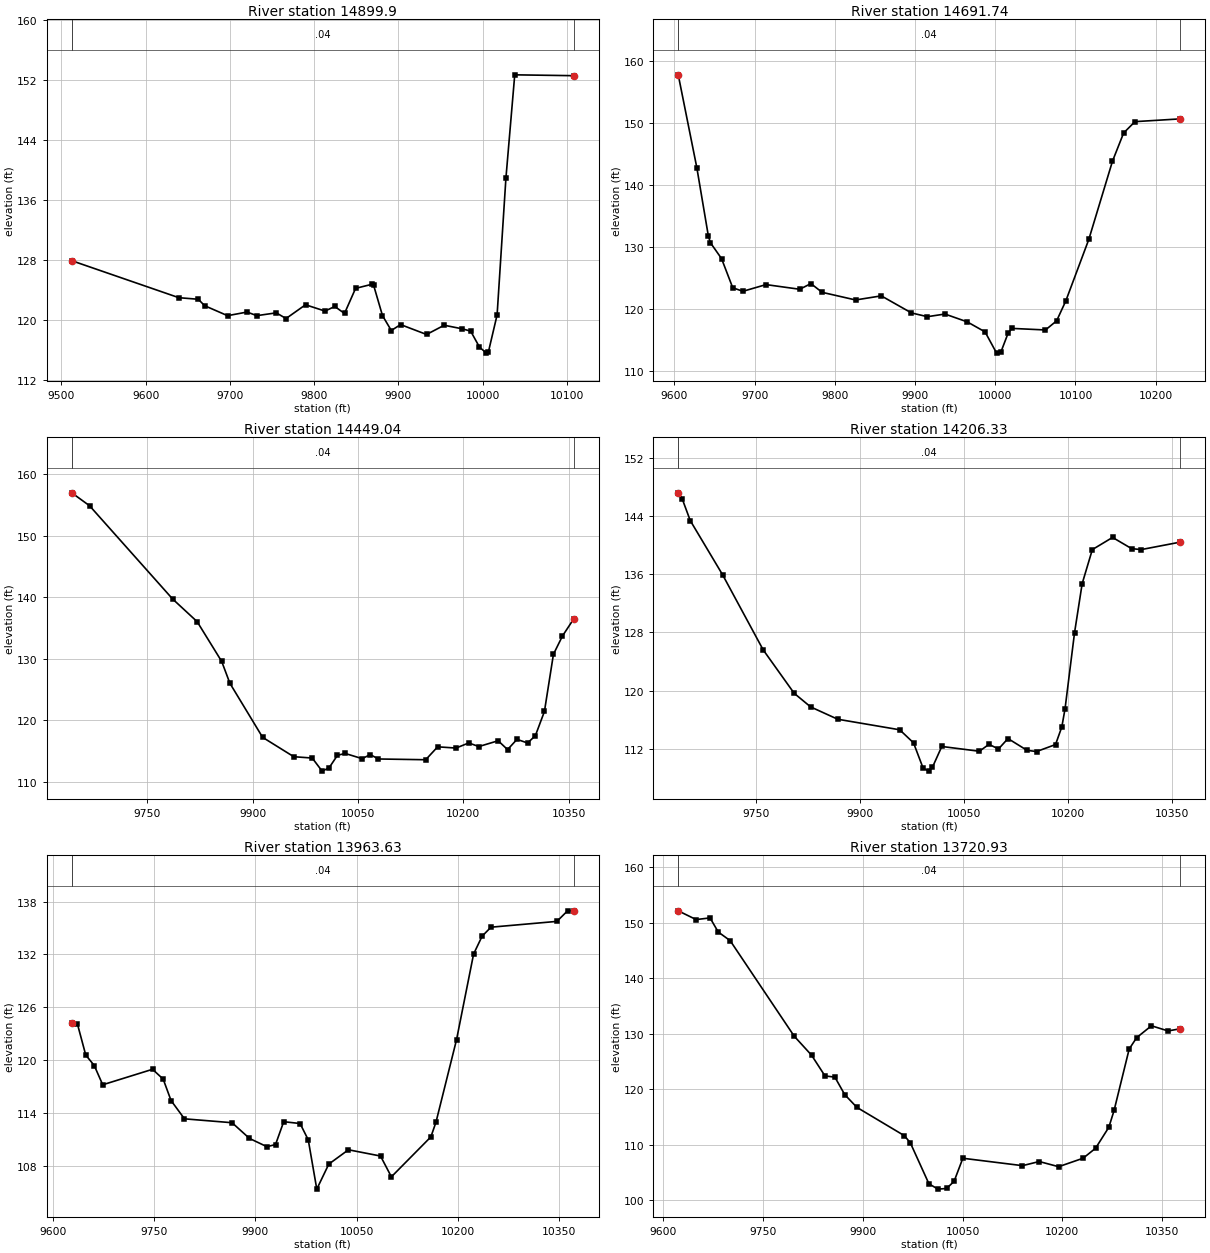
Type RM Length L Ch R = 1 , 14899.9,208.160300,208.160300,208.160300
XS GIS Cut Line= 3
905934.167574569805114.890364839905754.672048394804805.845893685
905684.434668586804577.964616975
#Sta/Elev= 30
9512.338 127.9249639.419122.98959662.548122.77859669.967121.92249697.241120.5887
9720.369121.07319731.934 120.5929755.062 120.9679766.627 120.2089789.755122.0454
9812.884121.20279824.448121.81739836.013120.88639849.164124.23299869.074124.7917
9870.613124.62749881.077120.60229891.541118.60869902.565119.40149933.398118.0812
9954.326119.31239975.255118.84619985.719118.53059996.183116.396510004.42115.5917
10006.65115.681810017.11120.688710027.58138.949410038.04152.726710108.19152.6114
#Mann= 3 , 0 , 0
9512.338    0.04       09512.338    0.04       010108.19    0.04       0
#XS Ineff= 2 , 0
       09843.535                       0
Bank Sta=9512.338,10108.19
Exp/Cntr=0.3,0.1

Type RM Length L Ch R = 1 ,14691.74,242.702100,242.702100,242.702100
XS GIS Cut Line= 2
906151.123036642804983.780589198905715.651281834804534.261358428
#Sta/Elev= 30
 9604.82157.71479627.992142.74319642.364 131.7159644.891130.63929658.814128.0722
9672.737123.37019685.481 122.7989714.225123.87779756.275123.12559770.197124.0415
 9784.12122.63389825.889121.39949857.945122.06199895.504119.30989915.433118.7033
9937.272119.13039965.118117.86439987.293116.250510001.67112.824710006.89112.9545
10016.04116.050110020.81116.814110062.58116.5601 10076.5118.0349 10087.9121.2327
10116.64131.175910146.12143.784110160.04148.339810174.13150.162210230.68150.6106
#Mann= 3 , 0 , 0
 9604.82    0.04       0 9604.82    0.04       010230.68    0.04       0
#XS Ineff= 2 , 0
       0                               0
Bank Sta=9604.82,10230.68
Exp/Cntr=0.3,0.1

Type RM Length L Ch R = 1 ,14449.04,242.702100,242.702100,242.702100
XS GIS Cut Line= 6
906376.329439823804750.361628914906279.320972867804688.262113498
905952.756386695 804488.55409912905919.807687722804462.225342197
905884.133393811804427.767277682905803.694165082 804332.39129643
#Sta/Elev= 30
9642.656156.93639667.981154.8371 9786.17139.69679821.117136.01219856.064129.5487
9867.713126.00599914.309117.22349958.643114.07919984.941113.8596    9999 111.736
10008.82112.257810020.83114.306910031.77 114.609   10056113.761110067.54114.4225
10079.09 113.70910146.42113.585910163.45115.683510189.58115.482110207.69116.3122
10222.09115.727710249.57116.670810262.95115.233110276.37116.896510291.48116.3043
10302.58117.504110315.42121.425310328.26130.716810341.11133.6852 10357.3136.4941
#Mann= 3 , 0 , 0
9642.656    0.04       09642.656    0.04       0 10357.3    0.04       0
#XS Ineff= 2 , 0
       0                               0
Bank Sta=9642.656,10357.3
Exp/Cntr=0.3,0.1

Type RM Length L Ch R = 1 ,14206.33,242.702100,242.702100,242.702100
XS GIS Cut Line= 6
906419.796707091804539.340543314906316.146839982804476.945909136
906182.136819775804403.992455704 906150.59131924804383.149686469
906060.995319865804292.194534839905853.732514252804098.524990388
#Sta/Elev= 30
9638.616147.17219644.215146.37819655.887143.36399702.575135.89919760.903125.6006
9805.497119.63729829.218117.76379868.241116.06899957.457114.62059977.357112.8266
9991.063109.3707    9999108.9417 10004.6109.475510018.07112.328710072.11111.6707
10085.98112.619510099.66111.986210113.35113.415610140.72111.800210154.41  111.63
10181.78112.590910190.84115.011910195.47117.491510209.15127.947410220.13134.6917
10234.78139.3729 10263.9141.044810291.27139.510710304.96139.371210361.44140.4021
#Mann= 3 , 0 , 0
9638.616    0.04       09638.616    0.04       010361.44    0.04       0
#XS Ineff= 2 , 0
       0                               0
Bank Sta=9638.616,10361.44
Exp/Cntr=0.3,0.1

Type RM Length L Ch R = 1 ,13963.63,242.702000,242.702000,242.702000
XS GIS Cut Line= 6
906581.540507379804407.526331062906488.789862767804337.072667766
906347.164459044804221.148337217906282.330603765804176.528641977
906191.037484285804117.685041991905987.635602952803959.603357378
#Sta/Elev= 30
9627.779 124.1799635.993124.15159648.488120.57099661.108119.37969673.666117.1902
9747.526118.94949763.314117.83439774.997115.3961 9794.89113.31899865.457112.8761
9891.302111.08989917.148110.1499  9929.9110.39519942.036112.99279966.306112.7852
9978.442110.92819991.081105.3272 10008.9108.171410038.03109.799910085.58109.0898
10101.69106.725410160.27111.269110167.89112.958610198.26122.303310223.59132.0534
10236.26134.087210249.37135.104110347.15135.764210362.91136.964510372.24136.9026
#Mann= 3 , 0 , 0
9627.779    0.04       09627.779    0.04       010372.24    0.04       0
#XS Ineff= 2 , 0
       09945.292                       0
Bank Sta=9627.779,10372.24
Exp/Cntr=0.3,0.1

Type RM Length L Ch R = 1 ,13720.93,242.702100,242.702100,242.702100
XS GIS Cut Line= 6
906723.689714778804290.798791972 906519.47338539804127.073572529
906427.628156932804032.373794336906325.824718283803904.463219607
906261.501301945803860.141851198906155.857981706803807.050072634
#Sta/Elev= 30
 9622.71152.16239649.619150.58419670.504 150.8889682.858148.34159700.716146.7909
9796.989129.56749823.076126.14119843.252122.40169858.091122.19029872.931119.0359
9891.093 116.745 9962.61111.62779971.511110.34329999.474102.954510013.06101.9992
10025.95102.114310037.27103.403810050.43107.564510140.04106.228610165.25106.9752
 10194.4106.0414 10231.2107.572310249.86 109.36710269.85113.1522 10277.7116.1771
 10300.4127.254710311.66129.302410333.83131.444310358.85130.511310377.24130.9088
#Mann= 3 , 0 , 0
 9622.71    0.04       0 9622.71    0.04       010377.24    0.04       0
#XS Ineff= 2 , 0
       0                               0
Bank Sta=9622.71,10377.24
Exp/Cntr=0.3,0.1

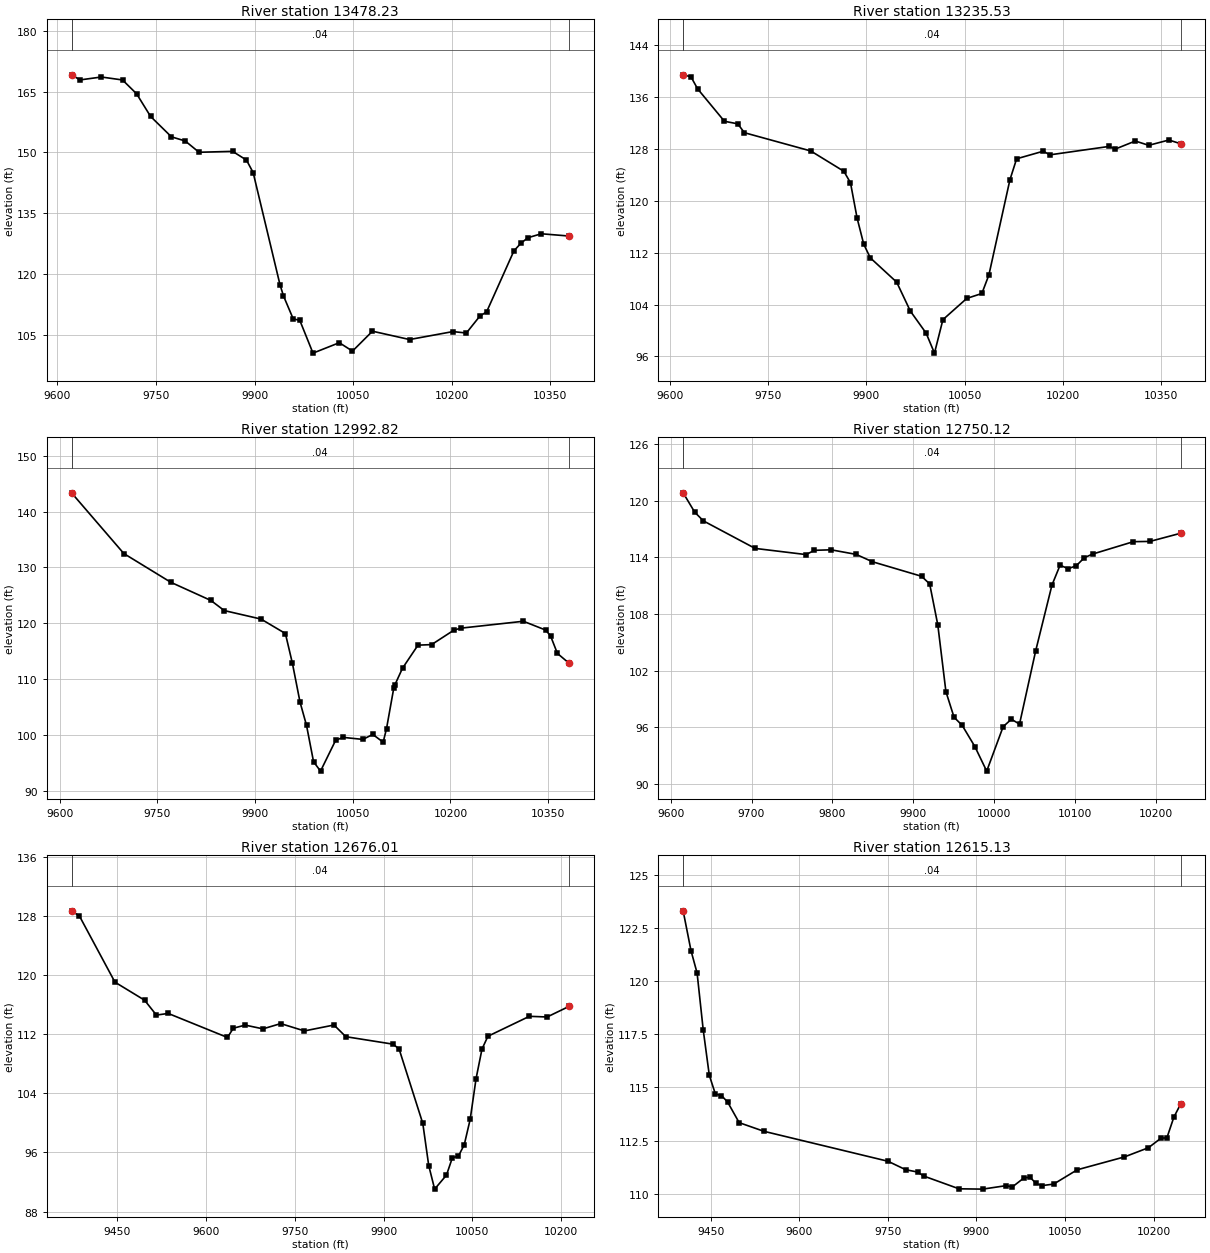
Type RM Length L Ch R = 1 ,13478.23,242.702100,242.702100,242.702100
XS GIS Cut Line= 6
906936.931686472803952.139024191906815.322785299 803904.41253892
906705.664883918803871.569587833906629.717313338803856.737232992
906446.916215427803836.713186737  906204.9281732803773.186995287
#Sta/Elev= 30
9621.496169.11589634.426167.86169666.936168.57869699.108167.84859720.465164.4537
9741.823158.86449773.526153.84369794.556152.8188 9815.51150.04089866.659150.2629
9887.714148.11639897.903145.03469938.659117.47089944.041114.66379958.841109.0056
9968.896108.63819988.961100.568210029.02103.136310049.05101.062210079.44 105.968
10135.96 103.91510201.86105.875810222.36105.519510242.86109.6753 10253.2110.7381
10294.72125.744310305.09127.587110315.89128.986210336.46129.9656 10378.5129.4113
#Mann= 3 , 0 , 0
9621.496    0.04       09621.496    0.04       0 10378.5    0.04       0
#XS Ineff= 2 , 0
       0                               0
Bank Sta=9621.496,10378.5
Exp/Cntr=0.3,0.1

Type RM Length L Ch R = 1 ,13235.53,242.702100,242.702100,242.702100
XS GIS Cut Line= 6
906866.645823724803657.845230918906551.283296403 803602.50468045
906436.739601772803669.988161872906362.604217779803694.051574265
906252.508775935 803696.36065204906137.677316682803672.775136182
#Sta/Elev= 30
9619.415 139.4419631.352139.14339641.602137.27559682.603132.27619703.007131.8822
9713.179130.51279814.668 127.6989865.358124.56199875.495122.78929885.633117.3401
9895.771113.31489905.909 111.1979946.175107.46069967.119102.99239991.25499.59138
10004.0396.5097110016.92 101.67310053.44104.949510076.53105.708110087.29108.5669
10119.44123.237210129.73126.488110170.49 127.65910180.54127.096910270.84  128.39
10280.96127.997810311.32129.229910331.86128.567710362.74129.384510380.56128.8167
#Mann= 3 , 0 , 0
9619.415    0.04       09619.415    0.04       010380.56    0.04       0
#XS Ineff= 2 , 0
       0                               0
Bank Sta=9619.415,10380.56
Exp/Cntr=0.3,0.1

Type RM Length L Ch R = 1 ,12992.82,242.702100,242.702100,242.702100
XS GIS Cut Line= 6
906952.390422877803607.361892753906637.715611377803524.657925708
906573.956834363803498.091071867906495.406526702803434.316156238
 906436.70164991803399.801937656906248.022198596803334.562305412
#Sta/Elev= 30
9618.012143.35069698.329132.47469770.495127.32379832.079124.06649852.607122.2559
9909.072120.73449946.461118.14629957.273112.79269968.923105.86839978.897 101.697
9989.70995.1779810000.4293.4947710023.6899.0272810035.1599.5415110065.4999.17623
10080.66100.073810096.6298.6767310101.76101.098410112.84108.327710114.43 108.905
10126.33111.930510150.11116.063310170.98116.157710205.83118.792710216.76119.1163
10311.98120.342910346.22118.763910353.76117.701610364.22114.583610381.97112.8405
#Mann= 3 , 0 , 0
9618.012    0.04       09618.012    0.04       010381.97    0.04       0
#XS Ineff= 2 , 0
       0                               0
Bank Sta=9618.012,10381.97
Exp/Cntr=0.3,0.1

Type RM Length L Ch R = 1 ,12750.12,74.112200,74.112200,74.112200
XS GIS Cut Line= 6
 906968.38605646803350.426815167906861.316270235803311.166315999
906764.537102927803284.993147482   906574.549604803258.120565023
906486.593913871803251.145090621906367.805137862803231.347722145
#Sta/Elev= 30
9615.401120.83179629.748118.78079640.465117.86019704.412114.94529767.392114.2918
9777.788114.74259798.382114.79749829.274114.31269849.551113.53059910.217111.9938
9920.264111.1861 9930.31106.84929940.35699.774569950.40397.063489960.44996.20657
9976.13693.960599990.78791.3564210011.1696.0697510021.3296.8542110031.3696.33426
10051.42104.121110071.49111.063410081.52113.166810091.55112.794210101.58113.1121
10111.62113.967110121.71114.344410172.21115.658810192.59115.684610230.49116.5479
#Mann= 3 , 0 , 0
9615.401    0.04       09615.401    0.04       010230.49    0.04       0
#XS Ineff= 2 , 0
       09919.952                       0
Bank Sta=9615.401,10230.49
Exp/Cntr=0.3,0.1

Type RM Length L Ch R = 1 ,12676.01,60.876200,60.876200,60.876200
XS GIS Cut Line= 2
907218.331447292803207.695871192 906378.13157051  803182.8929228
#Sta/Elev= 30
 9372.56128.68269385.898127.97959445.924119.03429495.946116.59669515.954114.5803
9535.963114.80169636.007111.55379646.011112.8047 9666.02113.22499696.033112.7161
9726.046113.42869766.063112.43739816.085113.23739836.094111.65639916.129110.6421
9926.133109.9811 9966.1599.924389976.15594.233019986.15991.0368910006.1792.93658
10016.17 95.298210026.1895.4799810036.1897.0375410046.19100.465210056.19105.9977
10066.19109.9859 10076.2111.717610146.23 114.41210176.24114.323810213.13115.7497
#Mann= 3 , 0 , 0
 9372.56    0.04       0 9372.56    0.04       010213.13    0.04       0
#XS Ineff= 2 , 0
       09903.382        10055.12       0
Bank Sta=9372.56,10213.13
Exp/Cntr=0.3,0.1

Type RM Length L Ch R = 1 ,12615.13,49.616900,49.616900,49.616900
XS GIS Cut Line= 6
907187.924902111803188.675965652907073.341568768803159.162076771
906666.463776559803132.867100373906557.088776559803126.790711492
906413.071709335803130.314687684906354.465050548803153.552223831
#Sta/Elev= 30
9402.988123.30619416.335121.43249426.662120.37889436.988117.71659447.314115.5733
9457.641114.68949467.967 114.6169478.294114.31659497.907113.34389539.691112.9382
9750.119111.5274 9780.18111.12829800.221111.02169810.242110.83639870.364110.2324
9910.449110.21719950.537 110.3829960.552110.31699980.583110.74869990.599110.7787
10000.61110.491510010.63110.380910030.66110.453510070.68111.126910150.71111.7329
10191.33112.164810212.84112.619610222.49 112.62310234.36113.600410245.69114.2099
#Mann= 3 , 0 , 0
9402.988    0.04       09402.988    0.04       010245.69    0.04       0
#XS Ineff= 2 , 0
       09899.534        10027.33       0
Bank Sta=9402.988,10245.69
Exp/Cntr=0.3,0.1

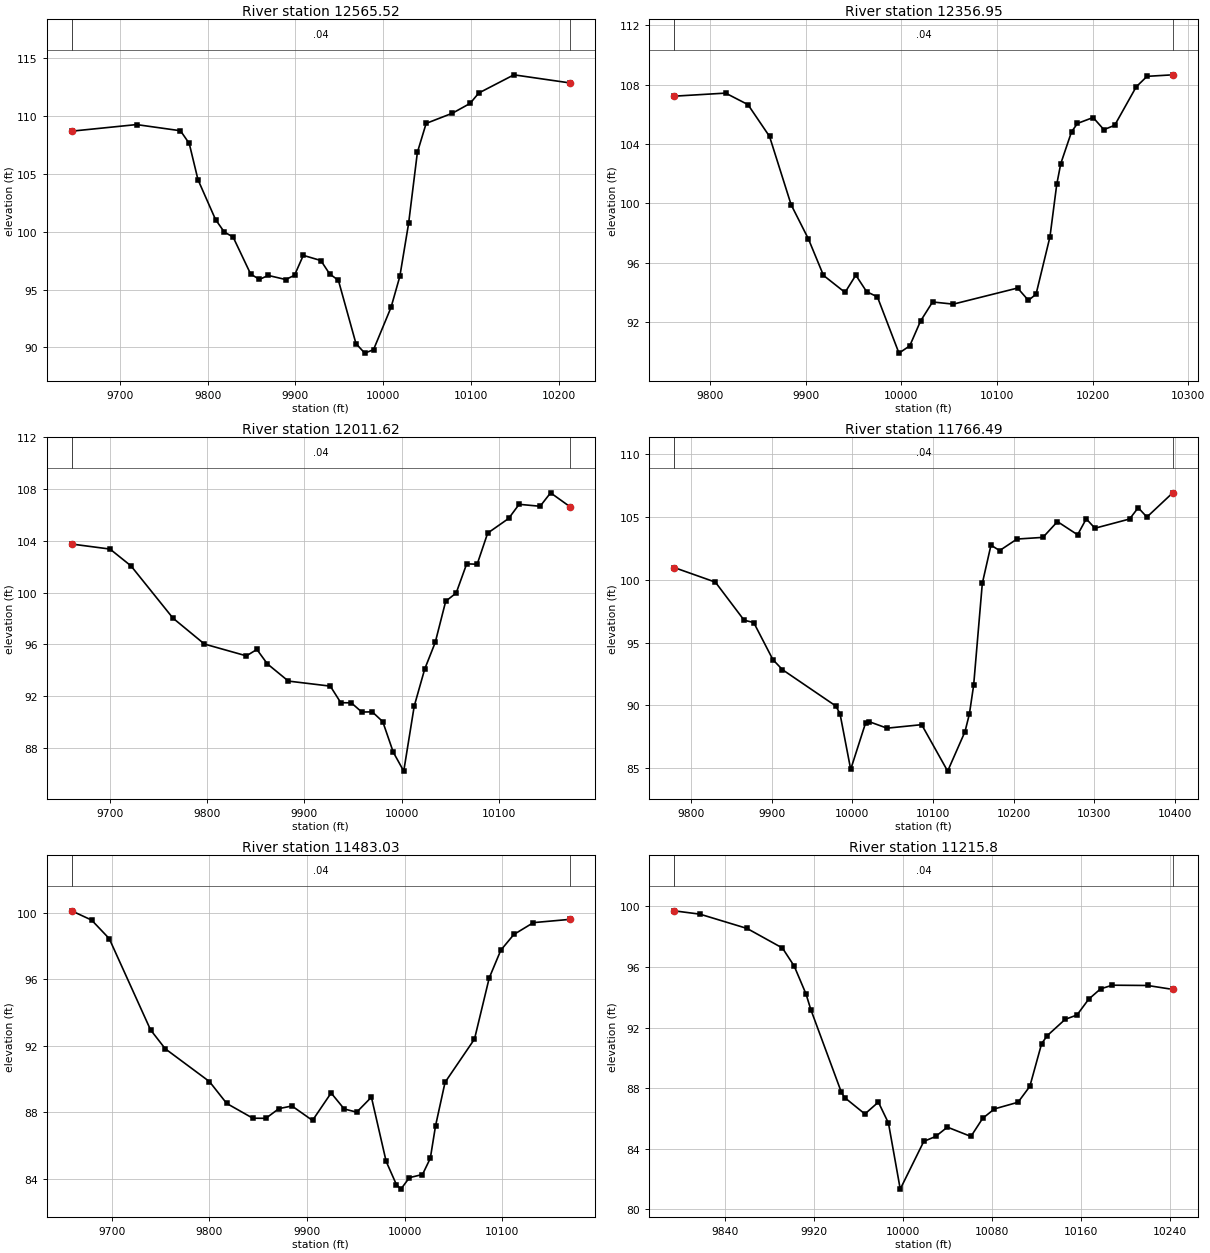
Type RM Length L Ch R = 1 ,12565.52,208.570400,208.570400,208.570400
XS GIS Cut Line= 2
906969.048383864803095.699132551 906400.91309113803075.995018352
#Sta/Elev= 30
9644.787108.6891 9718.88109.2591 9768.91108.72619778.916107.63059788.922104.4911
9808.934101.0496 9818.9499.969189828.94699.541579848.95896.344349858.96495.87652
 9868.9796.223699888.98295.866619898.98896.239199908.99497.957659929.00697.51006
9939.01296.356239949.01895.79992 9969.0390.335629979.036 89.50819989.04289.80134
10009.0593.4640110019.0696.1358410029.07100.717710039.07106.854110049.08109.3612
 10079.1110.244610099.11111.084510109.11111.987510149.14113.558710213.26 112.856
#Mann= 3 , 0 , 0
9644.787    0.04       09644.787    0.04       010213.26    0.04       0
#XS Ineff= 2 , 0
       09915.712        10020.43       0
Bank Sta=9644.787,10213.26
Exp/Cntr=0.3,0.1

Type RM Length L Ch R = 1 ,12356.95,345.323200,345.323200,345.323200
XS GIS Cut Line= 2
906953.423383864803029.854307146906491.183800531 802788.96889048
#Sta/Elev= 30
9762.564107.21389816.345107.42089839.721106.64579862.274104.50139884.82799.90319
9902.89997.599829918.65695.142669941.20993.995179952.48595.158929963.76294.04661
9975.03893.695799997.59189.9061410008.8790.3962210020.1492.0647310032.7393.35242
10054.3793.2056710121.6394.2897310132.9193.4598910140.9293.8759510155.4697.74211
10162.56101.277510166.74102.667710178.01104.8119 10184.2105.378810200.57105.7765
10211.84104.959310223.12105.251710245.67107.845210256.95108.5504 10283.8108.6521
#Mann= 3 , 0 , 0
9762.564    0.04       09762.564    0.04       0 10283.8    0.04       0
#XS Ineff= 2 , 0
       0                               0
Bank Sta=9762.564,10283.8
Exp/Cntr=0.3,0.1

Type RM Length L Ch R = 1 ,12011.62,245.129700,245.129700,245.129700
XS GIS Cut Line= 2
 906981.63518942802825.861251591906506.374772753802634.889029369
#Sta/Elev= 30
9660.795103.76349700.277103.37459721.832102.0733 9764.9498.037739797.27296.03385
 9840.3895.121059851.15795.616499861.93494.501399883.489 93.17219926.59792.78159
9937.374 91.50039948.15191.491929958.92990.779819969.706 90.79379980.48390.03704
 9991.2687.6791410002.0486.2131610012.8191.2369210023.59 94.102110034.3796.15418
10045.1599.3403510055.9299.97979 10066.7102.232210077.48102.202810088.25104.6053
10109.81105.740610120.59106.833210142.14106.681810152.92 107.72110172.99106.6393
#Mann= 3 , 0 , 0
9660.795    0.04       09660.795    0.04       010172.99    0.04       0
#XS Ineff= 2 , 0
       0                               0
Bank Sta=9660.795,10172.99
Exp/Cntr=0.3,0.1

Type RM Length L Ch R = 1 ,11766.49,283.461700,283.461700,283.461700
XS GIS Cut Line= 3
 906997.95076803 802723.58093642906784.795684809802586.294611633
906445.192670864802452.621084868
#Sta/Elev= 30
9778.849100.96139829.93899.802629865.62296.772739877.51696.590619901.306 93.6419
  9913.2   92.849979.37689.952869984.56889.343449997.844 84.909410016.3188.60356
10020.2588.7174210042.9288.18939 10085.988.4677910118.1484.7736310139.6487.91173
10145.1389.3268210150.3891.6031310161.1399.7013410171.88102.742110182.62102.3101
10204.12103.226810236.36103.360610254.35104.614310279.35103.567110290.09104.8348
10300.84104.087810343.83104.820710354.57105.720410365.32104.973910397.35106.9027
#Mann= 3 , 0 , 0
9778.849    0.04       09778.849    0.04       010397.35    0.04       0
#XS Ineff= 2 , 0
       0                               0
Bank Sta=9778.849,10397.35
Exp/Cntr=0.3,0.1

Type RM Length L Ch R = 1 ,11483.03,267.230700,267.230700,267.230700
XS GIS Cut Line= 2
907053.830284906802688.597262866906671.885840462  802350.0555962
#Sta/Elev= 30
9659.054 100.1339679.55399.575059697.57998.460169739.85792.966699754.93391.82423
9800.16189.849779817.84488.53225 9844.57 87.64249857.93387.634319871.29588.21885
9884.65888.378429905.69287.507579924.74689.161969938.10988.19981 9950.9288.00512
9965.99688.909559981.07285.04217 9991.5683.647369996.148 83.370210004.9284.06205
10018.2984.25045 10026.385.2296310031.6587.1827310041.3889.8021710071.5392.40935
 10086.696.0887810098.4697.7622310111.8398.7085210131.8399.4224110169.4499.61972
#Mann= 3 , 0 , 0
9659.054    0.04       09659.054    0.04       010169.44    0.04       0
#XS Ineff= 2 , 0
       0                               0
Bank Sta=9659.054,10169.44
Exp/Cntr=0.3,0.1

Type RM Length L Ch R = 1 , 11215.8,181.006800,181.006800,181.006800
XS GIS Cut Line= 2
907125.444868239802666.895873978906977.875423795802243.718790644
#Sta/Elev= 30
9794.29899.699179817.48799.47933 9859.8598.535759891.62197.245079902.21296.05222
9912.80394.21516 9917.1393.186719944.57487.73315  9947.587.381899965.75686.29515
 9977.8787.079269986.93785.694929997.52781.3383610018.7184.48947 10029.384.81124
10039.8985.4278110061.0784.8138910071.6686.0121810082.2586.6315210103.4387.06988
10114.02 88.116510124.6190.9350510129.7291.46712 10145.8 92.540110156.39 92.8247
10166.9893.8730610177.57 94.548710188.1694.7924110219.93 94.773710242.4794.51465
#Mann= 3 , 0 , 0
9794.298    0.04       09794.298    0.04       010242.47    0.04       0
#XS Ineff= 2 , 0
       0                               0
Bank Sta=9794.298,10242.47
Exp/Cntr=0.3,0.1