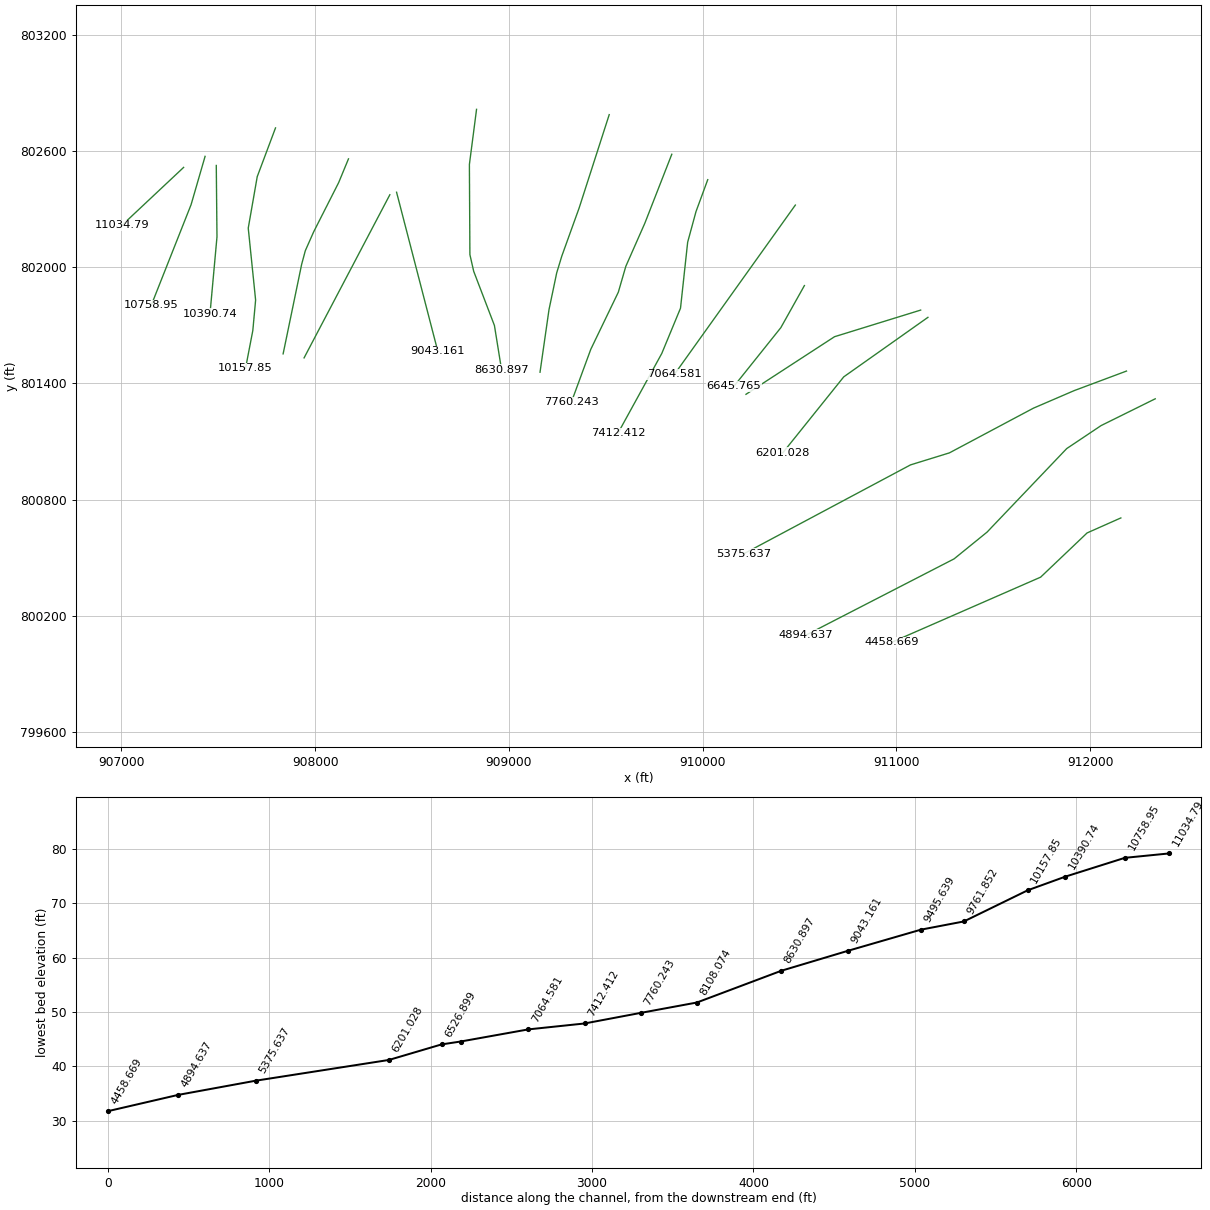
HEC-RAS study 13108_ras.prj: 13108

--- 13108_ras.g01 (geometry) --- (continued)

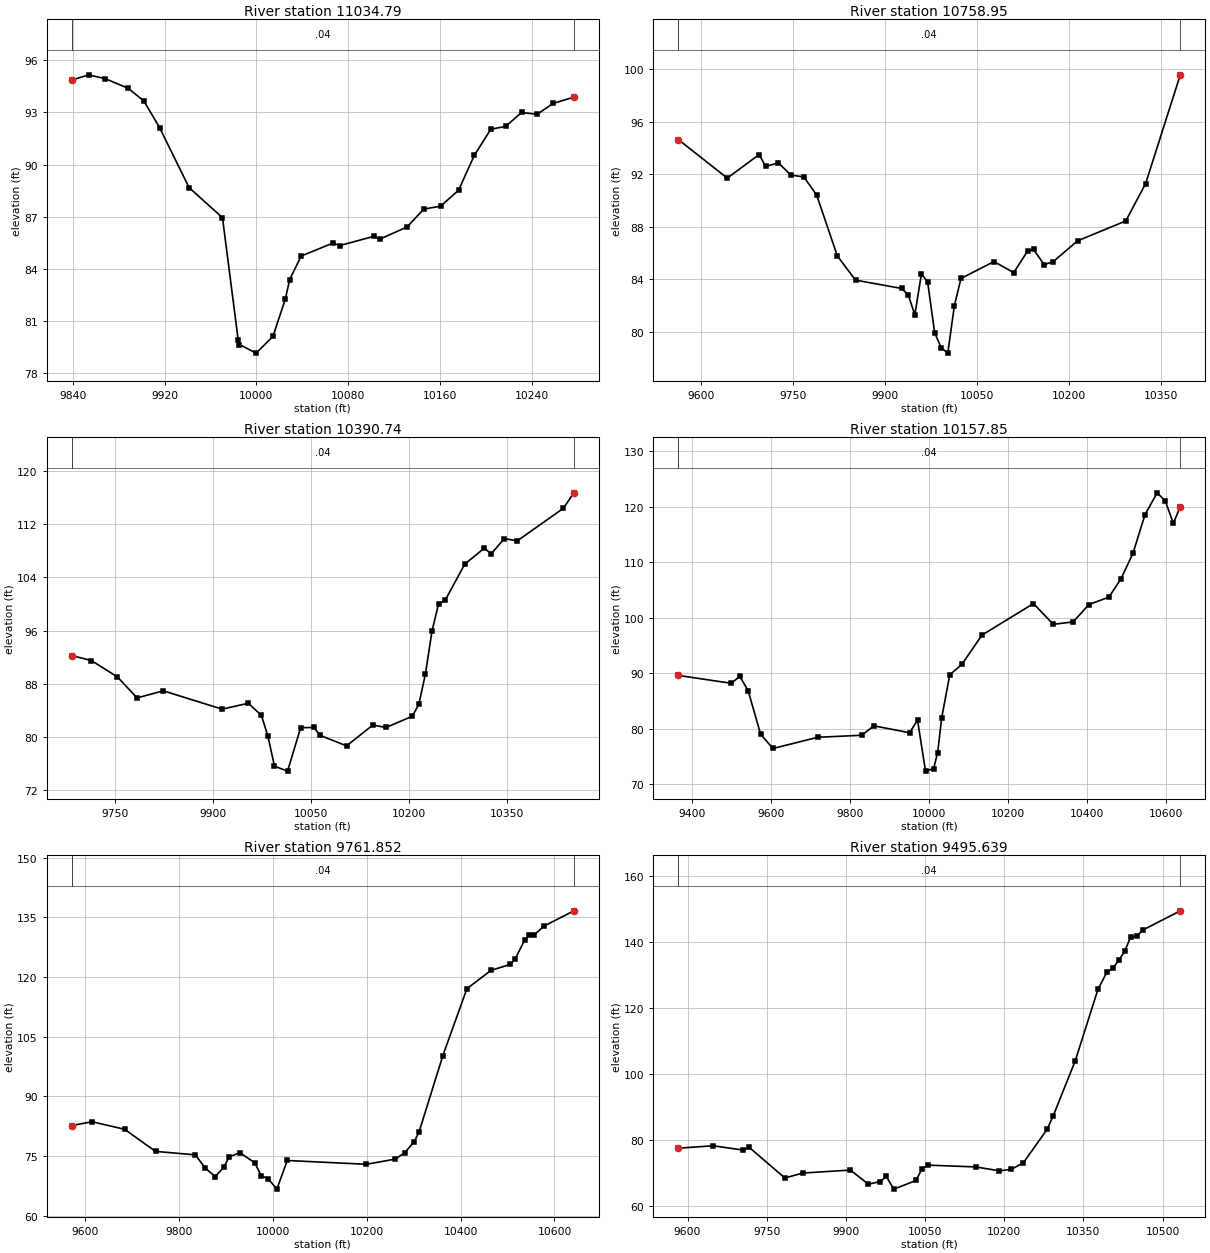
Type RM Length L Ch R = 1 ,11034.79,275.843700,275.843700,275.843700
XS GIS Cut Line= 2
907320.757368239802514.986151755907001.746951573802215.506985089
#Sta/Elev= 30
 9839.1594.85556 9853.7495.162629868.35194.940639888.19594.392519901.91193.66527
9915.62792.133639941.404 88.67919970.49186.951219984.20779.917089985.235 79.6614
9999.84679.1656310014.4680.1237310025.3682.2949210029.0783.3948910039.0784.74582
 10066.585.48536 10072.985.3519510102.12 85.873110107.6585.7196910131.3486.41756
10145.9587.4455110160.5687.6112810176.2388.5272310189.9590.5296410204.3992.03902
10217.3892.19752 10231.192.9992510244.81 92.894110258.53 93.517310276.7193.87803
#Mann= 3 , 0 , 0
 9839.15    0.04       0 9839.15    0.04       010276.71    0.04       0
#XS Ineff= 2 , 0
       0                               0
Bank Sta=9839.15,10276.71
Exp/Cntr=0.3,0.1

Type RM Length L Ch R = 1 ,10758.95,368.212300,368.212300,368.212300
XS GIS Cut Line= 3
907431.486530513 802571.84341955907359.230570099802322.560356123
907153.301082919801802.317441143
#Sta/Elev= 30
9563.19694.649599643.20391.704129695.26193.504199705.672 92.59539726.49592.86436
9747.31991.930559768.142 91.79779788.96590.41895 9822.7485.765149852.38183.92161
9927.665 83.2848 9938.4282.798089949.175 81.2701 9959.9384.404359970.08683.77891
 9981.4479.923389992.19578.7598910002.9578.35171 10013.781.9748410024.4684.04918
10078.2385.33528 10110.584.4961610133.1186.1407610142.7686.2656910160.2885.09723
10175.0385.3380410214.6286.9168310293.3388.43881 10325.691.2766710382.2699.58401
#Mann= 3 , 0 , 0
9563.196    0.04       09563.196    0.04       010382.26    0.04       0
#XS Ineff= 2 , 0
       09729.692                       0
Bank Sta=9563.196,10382.26
Exp/Cntr=0.3,0.1

Type RM Length L Ch R = 1 ,10390.74,232.885800,232.885800,232.885800
XS GIS Cut Line= 3
907489.291298844802524.877045281907492.904096864802156.371647171
907456.776116657801758.963864895
#Sta/Elev= 30
9684.20892.242059714.08691.501719754.08889.02901 9784.0985.885659824.09286.95384
9914.09684.199719954.09885.084359974.09983.268219984.09980.14364  9994.175.63832
 10014.174.89782 10034.181.4079910054.1181.4563810064.1580.2543110104.3178.68952
10144.4881.8092210164.5681.4468310204.73 83.131910214.7784.9046810224.8189.45845
10234.8595.8722910244.8999.9975510254.93100.522710285.06105.972710315.18108.3831
10325.22107.4739 10345.3109.799810365.39 109.46810435.68114.338610451.78116.6689
#Mann= 3 , 0 , 0
9684.208    0.04       09684.208    0.04       010451.78    0.04       0
#XS Ineff= 2 , 0
       09933.735                       0
Bank Sta=9684.208,10451.78
Exp/Cntr=0.3,0.1

Type RM Length L Ch R = 1 ,10157.85,396.000000,396.000000,396.000000
XS GIS Cut Line= 6
907794.976754672802718.752480975907700.691925499802467.329002206
907654.317395775802201.581525121907692.326268654801830.073503852
907677.882594818801672.870466049907640.273119215801477.709324794
#Sta/Elev= 30
9364.65389.634649498.937  88.2139520.39989.480129541.53486.887239573.23579.00852
9604.61876.473819717.98578.489479829.428 78.85259859.68780.552749950.19579.30482
9970.259 81.57499990.50772.3915710010.9972.8446110021.2275.7461210031.4582.01509
 10051.989.7462310082.5891.6256810133.2496.8906310263.68102.577310313.7498.83574
 10363.999.2682910404.19102.401410454.68103.736510485.13107.029210515.58  111.64
10546.07118.618310576.75122.5251 10597.2121.070110617.65117.043110635.33120.0504
#Mann= 3 , 0 , 0
9364.653    0.04       09364.653    0.04       010635.33    0.04       0
#XS Ineff= 2 , 0
       0 9965.24                       0
Bank Sta=9364.653,10635.33
Exp/Cntr=0.3,0.1

Type RM Length L Ch R = 1 ,9761.852,266.212800,266.212800,266.212800
XS GIS Cut Line= 6
908171.557648904802558.921344775908121.170753727802436.858703302
907991.771480347802182.013578229907948.789423134 802084.85241089
 907929.74249834 802013.67738713907834.273759985801552.467247839
#Sta/Elev= 30
9572.29882.636469615.69383.594529684.72681.69536 9750.6476.141629835.24975.27159
9856.41771.968919877.58569.801229896.10372.171129907.44974.756819930.14175.82381
9962.256 73.24669975.52469.989449990.25869.2894910009.0266.65341 10031.173.85408
10199.4872.89749 10260.674.1902210280.9775.7649410301.3478.5665410311.5380.96176
10362.46100.238510413.55117.027810464.72 121.63810505.66123.128910515.89124.4089
10536.36129.205410546.59 130.51810556.82130.554410577.29132.737210641.28136.6131
#Mann= 3 , 0 , 0
9572.298    0.04       09572.298    0.04       010641.28    0.04       0
#XS Ineff= 2 , 0
       0                               0
Bank Sta=9572.298,10641.28
Exp/Cntr=0.3,0.1

Type RM Length L Ch R = 1 ,9495.639,452.478600,452.478600,452.478600
XS GIS Cut Line= 2
908385.147687453802373.779211358 907942.43935412801531.765322469
#Sta/Elev= 30
9582.384 77.52679648.793 78.26239705.28376.962059716.581 77.82569784.36868.50901
9818.26270.006069908.64670.90868 9942.5466.635469965.13667.421339976.43468.98767
9990.97965.1419510032.92 67.755110044.2271.2666710055.4472.40358 10145.971.86003
10191.0970.6800910213.69 71.130710236.29 73.112710281.4883.2574110292.7887.28503
10334.79104.056910377.77125.659510394.46130.749910405.76131.975610417.05 134.409
10428.35 137.13910439.65141.454210450.95 141.64710462.25143.514110533.69149.3567
#Mann= 3 , 0 , 0
9582.384    0.04       09582.384    0.04       010533.69    0.04       0
#XS Ineff= 2 , 0
       0                               0
Bank Sta=9582.384,10533.69
Exp/Cntr=0.3,0.1

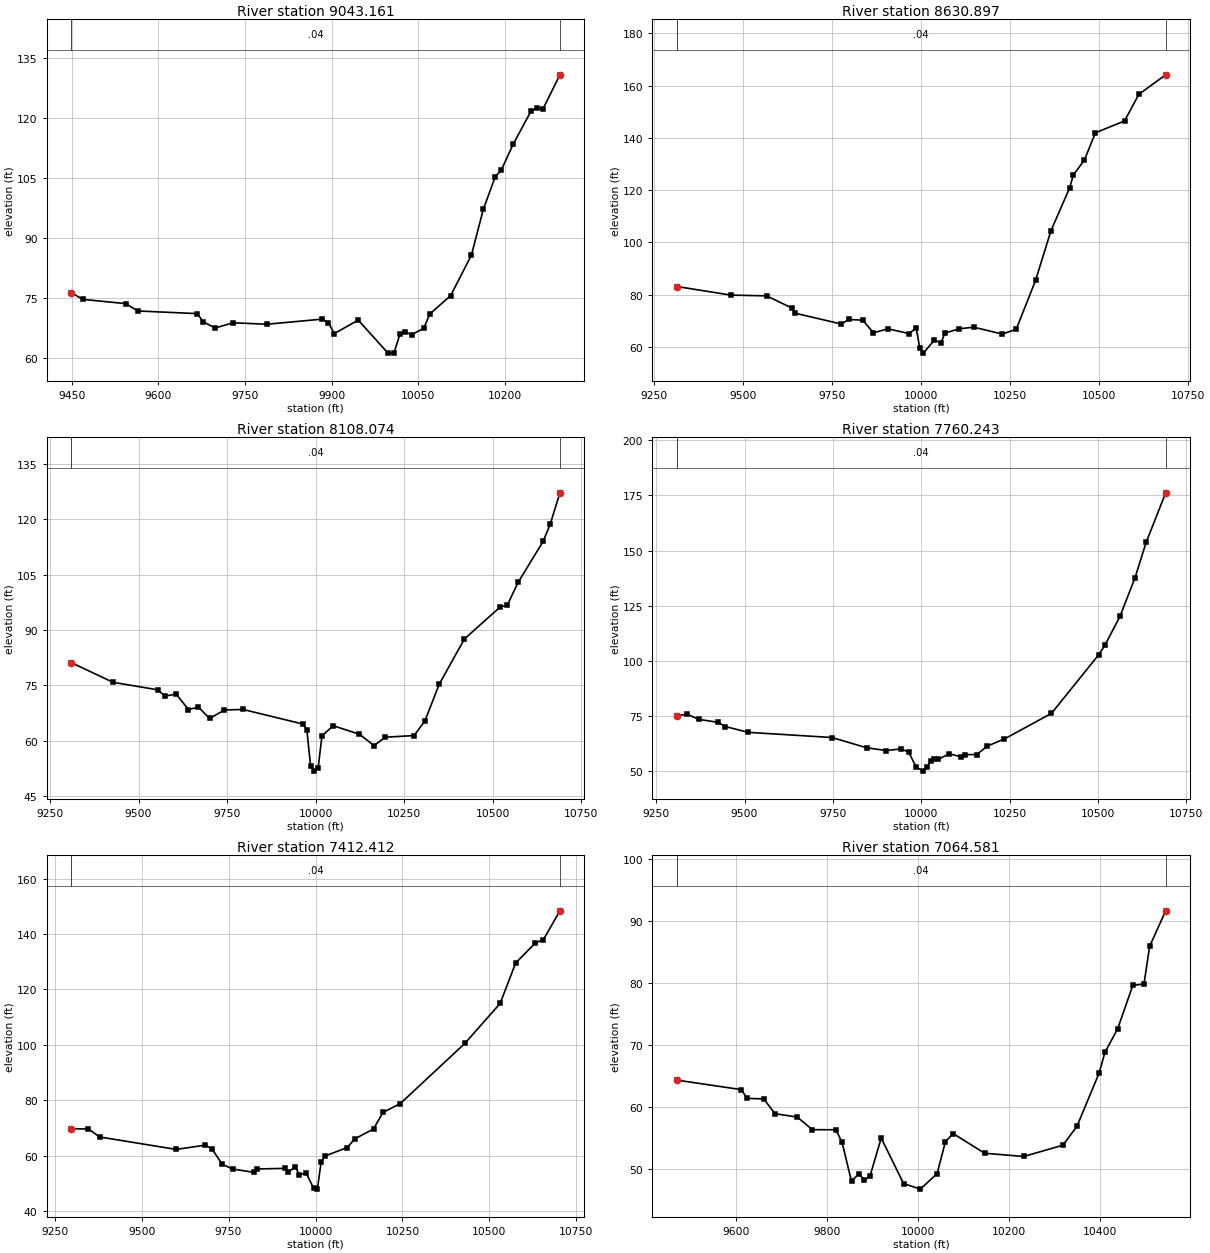
Type RM Length L Ch R = 1 ,9043.161,412.264000,412.264000,412.264000
XS GIS Cut Line= 2
908419.869909675802386.800044691908632.543520787801566.487544691
#Sta/Elev= 30
 9448.5376.390399468.971 74.68639543.36573.628819564.02671.794969667.33271.12831
9677.66369.061779698.32467.531459729.31668.842069787.74468.472459884.27569.75433
9894.60568.880899904.93666.144359946.25869.507749997.91261.2491810008.2461.25288
10018.5765.9793810026.8266.5385210039.2365.90155 10059.967.4407810070.2371.01927
10106.52 75.629410142.5485.76984 10163.297.2371410183.86 105.37610194.19 106.998
10214.85113.474510245.85121.768110256.18122.606510266.51122.293310295.96130.8463
#Mann= 3 , 0 , 0
 9448.53    0.04       0 9448.53    0.04       010295.96    0.04       0
#XS Ineff= 2 , 0
       0                               0
Bank Sta=9448.53,10295.96
Exp/Cntr=0.3,0.1

Type RM Length L Ch R = 1 ,8630.897,522.822900,522.822900,522.822900
XS GIS Cut Line= 6
908832.671371461802814.671991029908795.751958951802530.206183578
908798.366328363802064.768390357908817.996452037801978.575462323
908924.973878618 801698.93447378908961.816299217801470.137934356
#Sta/Elev= 30
9313.31683.077759465.08179.794429565.56679.494539635.66574.887769645.66872.86361
9775.71968.707229795.73570.458859835.76770.195849865.79165.334989905.82366.90005
9965.84565.070739985.89367.206519995.91759.3928710005.9457.58169   1003662.44847
10056.0161.6467410066.0165.20792 10106.566.9160610148.1367.4938110227.3864.87741
10266.7566.6957410321.0785.4029110363.94104.282710416.72120.791710427.19125.7118
 10458.5131.550410489.32141.925610571.04146.436810611.42156.6497 10686.6 164.098
#Mann= 3 , 0 , 0
9313.316    0.04       09313.316    0.04       0 10686.6    0.04       0
#XS Ineff= 2 , 0
       0                               0
Bank Sta=9313.316,10686.6
Exp/Cntr=0.3,0.1

Type RM Length L Ch R = 1 ,8108.074,347.831000,347.831000,347.831000
XS GIS Cut Line= 6
909517.443814554802787.251918519 909362.27135431802305.797038525
909272.615079099 802056.90517428909246.390718686801970.501853339
 909206.69018118801781.085967247909160.280449423801457.845671542
#Sta/Elev= 30
9309.55681.177429427.87575.829229553.97173.788399574.95372.104279606.42672.61701
9641.02268.443589669.37269.087459700.845  66.014 9742.8168.324329795.265 68.4632
9964.82464.499629975.48962.923849986.15553.05394 9996.8251.7447310007.4752.60215
10018.11 61.306310050.0664.0433510123.7661.7606110165.5758.6678510196.4860.93615
10278.4361.3869210308.9765.3506110349.6975.35619 10420.687.5653610521.6896.24869
10541.87 96.729310572.15102.903710642.81113.9951   10663 118.68110690.41127.1896
#Mann= 3 , 0 , 0
9309.556    0.04       09309.556    0.04       010690.41    0.04       0
#XS Ineff= 2 , 0
       0                               0
Bank Sta=9309.556,10690.41
Exp/Cntr=0.3,0.1

Type RM Length L Ch R = 1 ,7760.243,347.831100,347.831100,347.831100
XS GIS Cut Line= 6
909840.410886383802582.708280399909701.450967567802227.260053601
909603.129529825802004.298749983909564.513505609801871.017338649
 909422.37742326801576.212207955909321.856037173801302.743872899
#Sta/Elev= 30
 9308.4475.073599338.19175.636779370.40273.347929424.08772.010699445.56170.09597
9509.98367.451759747.20165.105119845.56460.45618 9900.2159.188179943.57459.92565
9964.67458.408739985.40351.6659710005.8549.8373510016.1151.5028910026.3854.54115
10036.7155.5589510047.32 55.123210079.3757.6852310112.34 56.367110123.3357.33877
10156.8757.3493610186.8361.2049210235.3664.4501110368.4976.06672 10501.8102.6151
 10519.7107.020510562.21120.072810604.53137.514810636.26153.678710691.54176.2108
#Mann= 3 , 0 , 0
 9308.44    0.04       0 9308.44    0.04       010691.54    0.04       0
#XS Ineff= 2 , 0
       0                               0
Bank Sta=9308.44,10691.54
Exp/Cntr=0.3,0.1

Type RM Length L Ch R = 1 ,7412.412,347.831000,347.831000,347.831000
XS GIS Cut Line= 6
910025.970002463802451.517506888909965.383828227 802286.96931937
909922.330507495802128.908902898909885.418666955801788.327874006
909788.749650271801554.611143212909562.597950715801143.153541055
#Sta/Elev= 30
9297.39869.676829347.23569.610989379.37666.724219599.52362.22738  9681.363.73517
9701.61662.545929731.87756.834169762.08355.154539822.24853.956049832.25355.15789
9912.294 55.38759922.29954.154649942.42155.955529952.50153.131629973.18153.62545
9994.48548.2832410005.3647.88952 10016.257.7144410027.0359.8355910091.3262.90327
10112.7366.03235 10166.869.6110710193.7875.5754410243.9878.7964610429.18100.4796
10530.71114.919410575.35129.506510632.26136.803110655.03137.944910702.66148.3678
#Mann= 3 , 0 , 0
9297.398    0.04       09297.398    0.04       010702.66    0.04       0
#XS Ineff= 2 , 0
       0                               0
Bank Sta=9297.398,10702.66
Exp/Cntr=0.3,0.1

Type RM Length L Ch R = 1 ,7064.581,418.816100,418.816100,418.816100
XS GIS Cut Line= 2
910478.119342932802320.495997543909853.682744374801446.284759562
#Sta/Elev= 30
9470.16864.346799612.10262.812059624.391 61.40749661.258 61.32249685.83658.94933
9734.99258.389259768.01456.373069819.62856.355729833.30454.341749854.03748.03558
9870.171 49.2966 9882.4648.234159894.74948.919079919.32755.030529968.48447.69727
10005.3546.8043610042.2249.3063510060.4954.46055 10077.755.7357310146.52 52.5786
10232.5452.0553610318.5653.8724910349.44 56.8981 10398.665.5479610410.8968.79876
   1043972.5973710472.3379.5929610496.9179.81053 10509.285.8517510544.4991.58644
#Mann= 3 , 0 , 0
9470.168    0.04       09470.168    0.04       010544.49    0.04       0
#XS Ineff= 2 , 0
       09886.078                       0
Bank Sta=9470.168,10544.49
Exp/Cntr=0.3,0.1

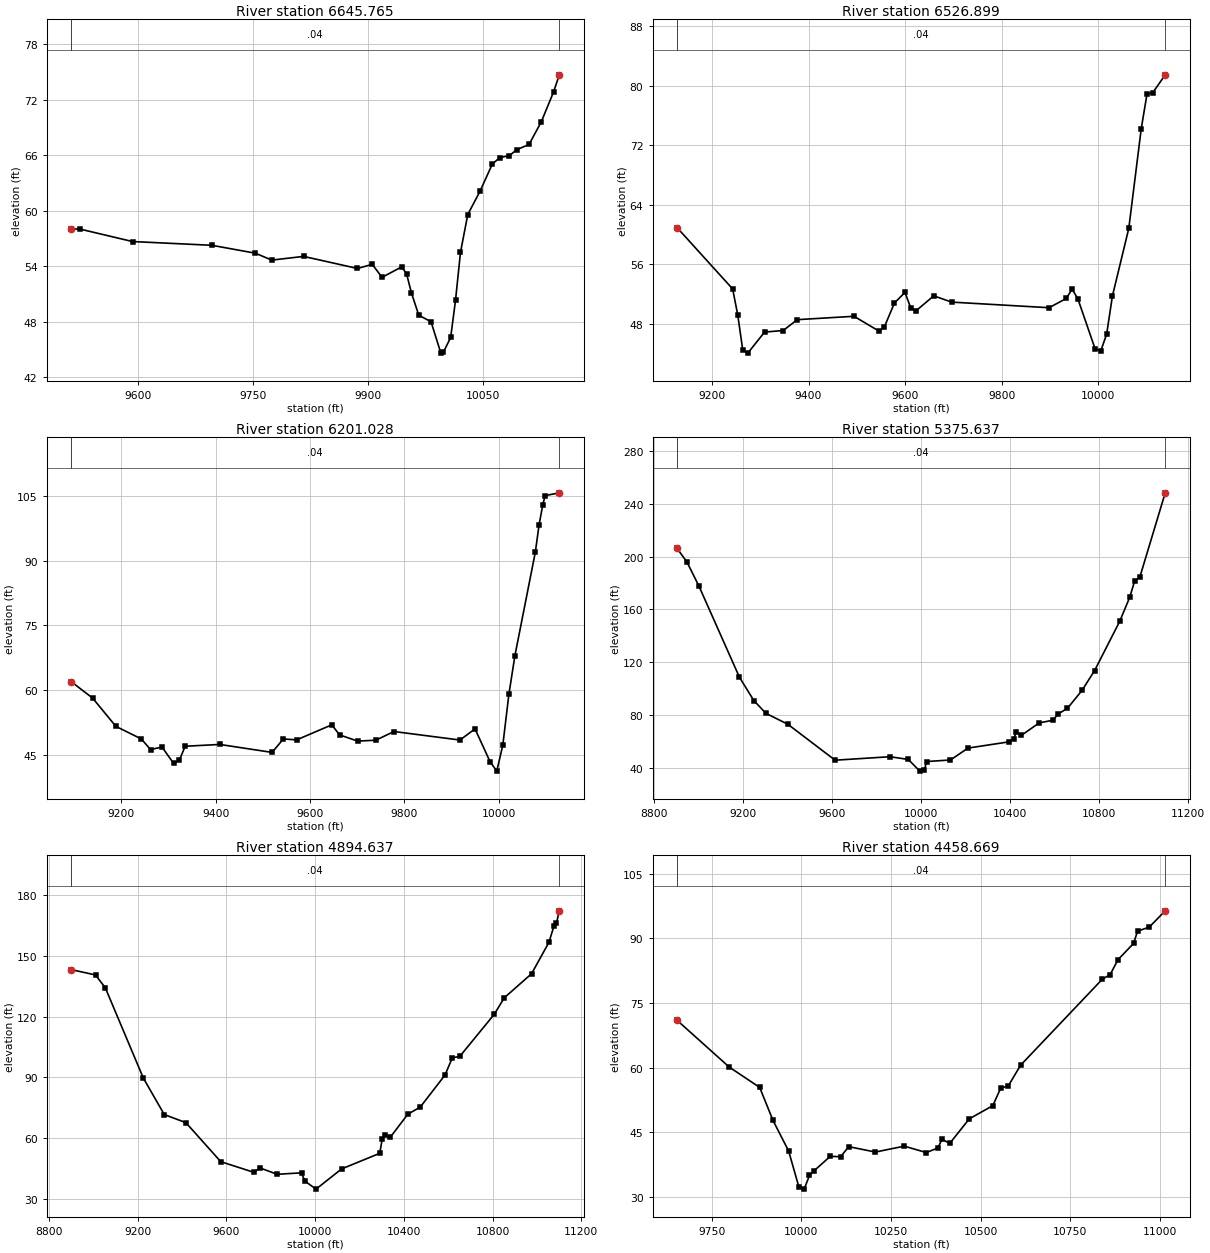
Type RM Length L Ch R = 1 ,6645.765,118.865100,118.865100,118.865100
XS GIS Cut Line= 3
910524.904631898801905.029211358 910403.37685412801688.015322469
910160.321298564801384.195878025
#Sta/Elev= 30
9512.48258.019249523.976 58.01069592.74456.659339696.48556.250859753.20155.39732
9774.61654.649539816.29355.049299886.67153.742079905.93754.189859918.74352.77957
9944.35553.916859950.70253.181649957.16251.09067 9966.7148.683539982.718 47.9753
 9995.58 44.57579998.72544.6449910008.3946.2725810014.73 50.301610021.1955.47714
10030.7459.5855210046.7562.1065110062.76 65.042310072.4265.7447810085.2265.96758
10094.7766.6051210110.7867.1701810126.79 69.6272 10142.872.8499110150.2974.71126
#Mann= 3 , 0 , 0
9512.482    0.04       09512.482    0.04       010150.29    0.04       0
#XS Ineff= 2 , 0
       0                               0
Bank Sta=9512.482,10150.29
Exp/Cntr=0.3,0.1

Type RM Length L Ch R = 1 ,6526.899,325.871300,325.871300,325.871300
XS GIS Cut Line= 3
911125.035659038801778.485029995910680.436800865801641.108978312
 910223.34921072801343.877157399
#Sta/Elev= 30
9127.76760.939289242.93552.676549253.40249.204129263.86844.456849274.33544.04186
9308.93846.87144  9347.647.086439376.685  48.5459494.13149.000019546.46446.97668
 9556.9347.558119577.86350.797399599.59152.206239611.51950.137939622.65549.74601
9659.23351.75471 9696.0350.907529897.809 50.15289933.58551.397269945.513 52.6542
9957.44151.360199993.22644.6076410005.1544.3794110017.0846.5933810029.01 51.7207
 10062.960.8278410088.6574.2211710100.5878.8916410112.5179.0810110138.3481.48937
#Mann= 3 , 0 , 0
9127.767    0.04       09127.767    0.04       010138.34    0.04       0
#XS Ineff= 2 , 0
       09661.835                       0
Bank Sta=9127.767,10138.34
Exp/Cntr=0.3,0.1

Type RM Length L Ch R = 1 ,6201.028,825.391400,825.391400,825.391400
XS GIS Cut Line= 3
911162.501854951801741.018834081910727.893982355801433.796027591
910413.177936682801041.649843697
#Sta/Elev= 30
9093.50661.961019139.43258.100159188.41751.572329242.52548.642929261.894 46.2008
9286.38646.757849310.87942.982339323.12543.726789335.37146.957939408.84947.37084
9519.70845.526489543.55748.655099571.67948.429639646.33851.92692 9662.6649.59235
9701.126 48.14749739.59348.356789778.05950.371189917.94448.398259949.89850.98434
9981.85143.358589996.03641.1846110008.8647.2432710021.6858.97716 10034.567.98853
10077.7191.9487510085.7998.3670210093.69103.017410098.61 105.08810128.55105.7356
#Mann= 3 , 0 , 0
9093.506    0.04       09093.506    0.04       010128.55    0.04       0
#XS Ineff= 2 , 0
       09629.271                       0
Bank Sta=9093.506,10128.55
Exp/Cntr=0.3,0.1

Type RM Length L Ch R = 1 ,5375.637,481.000000,481.000000,481.000000
XS GIS Cut Line= 6
912187.313983605801463.754171357911916.613706097801362.537386374
911705.970102986801271.782559511911273.480872965801041.549868837
911072.592493146800979.479028734910213.884229925800521.655985803
#Sta/Elev= 30
8903.666206.3304 8948.68195.7905 9001.87177.74559183.694108.67659248.57490.90677
9302.71481.214599401.21572.928039613.634 45.65729859.84448.283959942.38646.24165
9994.10637.3669910014.4437.8485810024.6244.6397610131.7745.81452 10210.754.84303
10393.6759.5352810416.5462.0153810427.9767.1607910450.8264.54959 10530.473.92938
10593.0475.9995510614.0780.5932610657.09 84.950410722.8798.6091310779.27113.6428
10892.09150.967410937.21169.270510959.55181.831210982.34184.442811096.41248.3765
#Mann= 3 , 0 , 0
8903.666    0.04       08903.666    0.04       011096.41    0.04       0
#XS Ineff= 2 , 0
       0                               0
Bank Sta=8903.666,11096.41
Exp/Cntr=0.3,0.1

Type RM Length L Ch R = 1 ,4894.637,435.968000,435.968000,435.968000
XS GIS Cut Line= 6
912335.622387291 801320.54615351912056.461879204801182.462873116
911878.752992557801063.620553936 911467.51779463800632.344342131
911297.431161509800494.364941254910533.461016289800101.094969771
#Sta/Elev= 30
8899.291143.27089009.613140.60099054.091134.16519224.999 89.67059319.51971.61322
9417.09367.601659574.26748.32273 9724.1343.036649750.27545.264359828.71142.08182
9938.50342.810029953.11538.7472410003.9234.7531110119.0944.7385210290.9352.44105
10302.6859.6671310314.4361.2655410337.9360.2795210417.6771.7782710473.8875.30438
10585.2591.1138610618.6699.6759210652.07100.353310807.99121.235310852.54129.3012
10975.68 141.20711054.17156.7553 11076.6164.743911087.81166.102711100.75172.3042
#Mann= 3 , 0 , 0
8899.291    0.04       08899.291    0.04       011100.75    0.04       0
#XS Ineff= 2 , 0
       0                               0
Bank Sta=8899.291,11100.75
Exp/Cntr=0.3,0.1

Type RM Length L Ch R = 1 ,4458.669,738.878200,738.878200,738.878200
XS GIS Cut Line= 4
912158.176757775800705.663435004911984.062304644800628.279233612
 911744.17128033800399.995839507910974.198476483800063.374563453
#Sta/Elev= 30
9653.17670.978439798.914 60.10179883.83155.37682    992147.698789964.51940.61673
9993.53132.1483410008.0431.7521410022.5434.9258210035.6836.0221610080.5739.36109
10109.5839.2870910132.3141.61743 10206.740.3640410287.19 41.738510348.5840.24618
10381.3241.3325110392.2443.3360410414.0642.3800510468.6348.0867210534.1251.13399
10555.9555.1726610577.7755.7801710611.7260.5392810839.7180.5125210861.5381.57471
10883.3685.0485410927.0288.8428210937.9391.6738310970.6792.61943 11015.2 96.3988
#Mann= 3 , 0 , 0
9653.176    0.04       09653.176    0.04       0 11015.2    0.04       0
#XS Ineff= 2 , 0
       0                               0
Bank Sta=9653.176,11015.2
Exp/Cntr=0.3,0.1