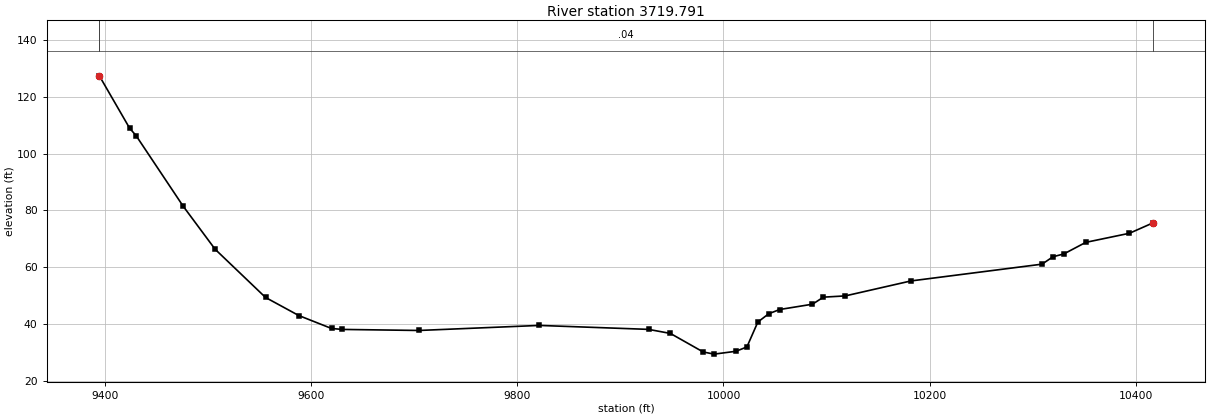
HEC-RAS study 13108_ras.prj: 13108

--- 13108_ras.g01 (geometry) --- (continued)

Type RM Length L Ch R = 1 ,3719.791,0.000000,0.000000,0.000000
XS GIS Cut Line= 3
912126.210456812 800129.17258989 911979.72420648800048.508023412
911173.726149926799764.038121099
#Sta/Elev= 30
9394.518127.32429423.899108.90669430.147106.29679475.81181.483889506.82466.32942
9555.72249.375729587.96443.016619619.77838.455399630.38238.121529704.61437.75507
9821.26539.52891 9927.3138.138769948.51936.713459980.33330.191979990.93829.43294
10012.1530.4356210022.7531.9605610033.3640.7206110043.9643.6455710054.5645.12781
10086.3846.9970510096.98 49.474410118.1949.9137910181.8255.1738510309.0761.07851
10319.6863.6809110330.2864.6823910351.4968.7444410393.9171.9487310416.4775.56127
#Mann= 3 , 0 , 0
9394.518    0.04       09394.518    0.04       010416.47    0.04       0
#XS Ineff= 2 , 0
       0                               0
Bank Sta=9394.518,10416.47
Exp/Cntr=0.3,0.1